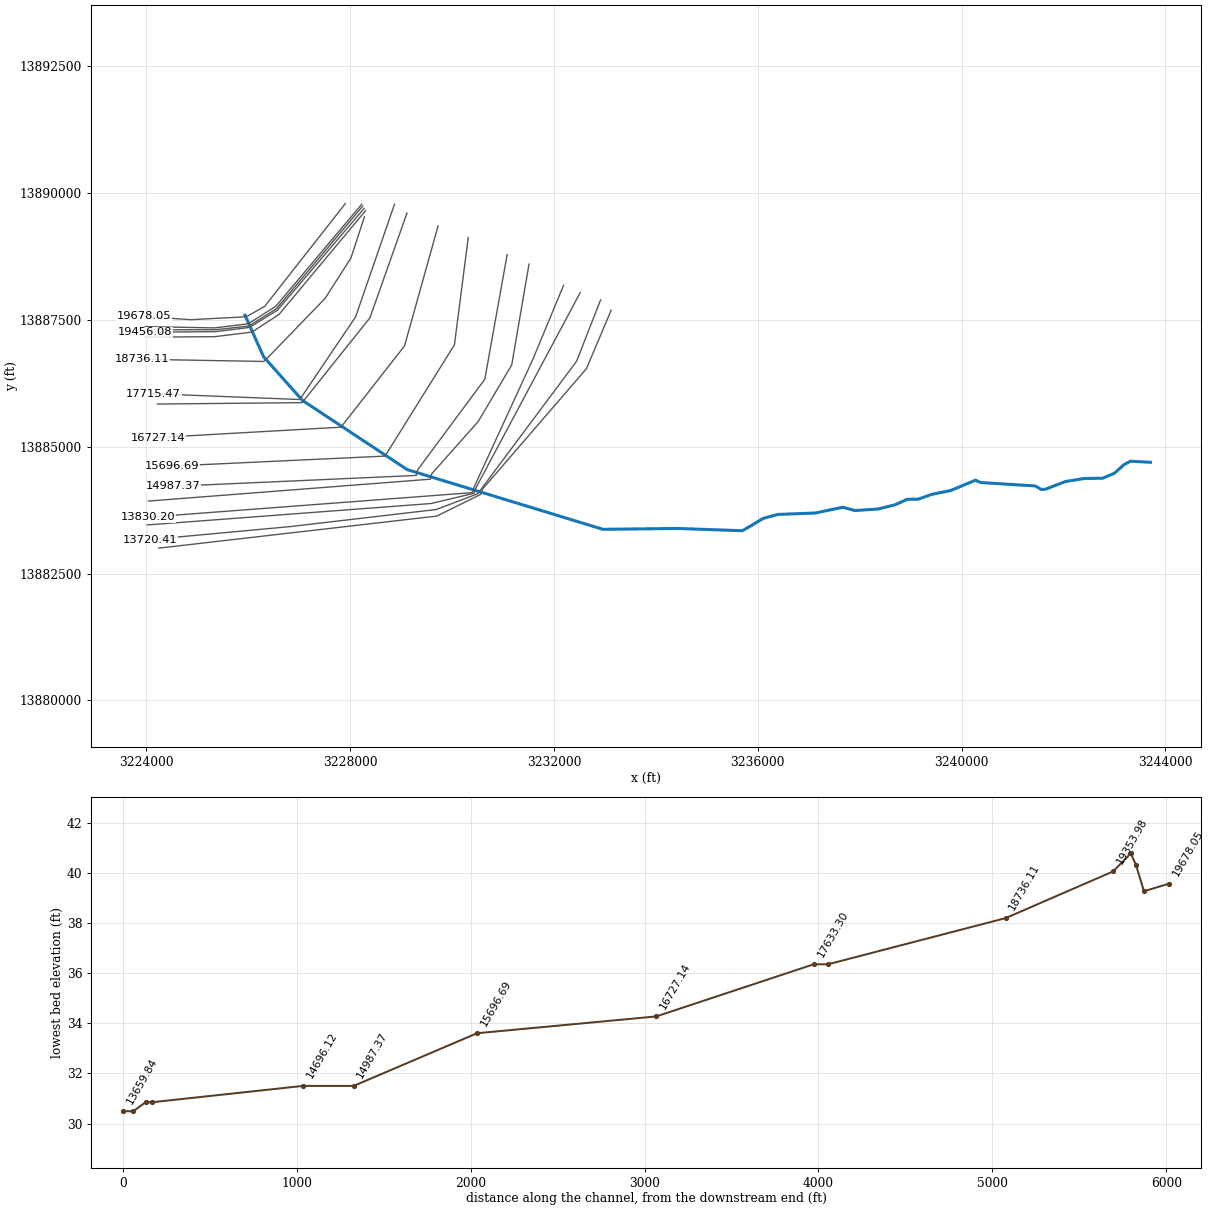
--- Q122-00-00.prj (project) ---

Proj Title=Q122-00-00
Current Plan=p03
Default Exp/Contr=.3,.1
English Units
Geom File=g01
Flow File=f01
Flow File=f02
Plan File=p01
Plan File=p03
Y Axis Title=Elevation
X Axis Title(PF)=Main Channel Distance
X Axis Title(XS)=Station
BEGIN DESCRIPTION:
HCFCD Unit Q122-00-00
Flood Hazard and Floodway Model
10, 2, 1, & 0.2% Events
Filename: Q122.prj
Prepared by: Costello, Inc. Date: August 21, 2003
Reviewed by: _________ Date:____________
Status: Final
END DESCRIPTION:
DSS Export Rating Curves= 0
DSS Export Rating Curve Sorted= 0
DSS Export Volume Flow Curves= 0
DXF OffsetX= 0
DXF OffsetY= 0
DXF ScaleX= 1
DXF ScaleY= 10

--- Q122-00-00.p03 (plan) ---

Plan Title=Floodway
Version=Version 3.0.1  Mar 2001
Short Identifier=Floodway0607
Geom File=g01
Flow File=f02
Subcritical Flow
K Sum by GR= 0
Std Step Tol= 0.01
Critical Tol= 0.01
Num of Std Step Trials= 20
Max Error Tol= 0.3
Flow Tol Ratio= 0.001
Split Flow NTrial= 30
Split Flow Tol= 0.02
Split Flow Ratio= 0.02
Log Output Level= 0
Friction Slope Method= 1
Unsteady Friction Slope Method= 2
Parabolic Critical Depth
Global Vel Dist= 0 , 0 , 0
Global Log Level= 0
CheckData=True
Encroach Param=-1 ,0,0, 2
Encroach River=Q122-00-00
Encroach Reach=Q122-00-00_0001
Encroach Node=19678.05
       1 2668.69 3029.68
Encroach Node=19531.76
       1 2871.28 3284.64
Encroach Node=19485.76
       1    2849    3375
Encroach Node=19460.76
       1    2880    3393
Encroach Node=19456.08
       1    2900    3405
Encroach Node=19353.98
       1    3050    3460
Encroach Node=18736.11
       1    3055    3725
Encroach Node=17715.47
       1    3780    4825
Encroach Node=17633.30
       1    3795  4780.9
Encroach Node=16727.14
       1    3995  4852.9
Encroach Node=15696.69
       1 4304.58 5125.02
Encroach Node=14987.37
       1 4501.78    5260
Encroach Node=14696.12
       1 4501.78    5369
Encroach Node=13830.20
       1 4201.78 4996.44
Encroach Node=13790.57
       1 4208.79 4928.55
Encroach Node=13760.57
       1 4158.99 4848.55
Encroach Node=13720.41
       1 4065.16 4763.86
Encroach Node=13659.84
       1 3990.43    4494
Encroach Node=12683.52
       1 4065.13 4436.34
Encroach Node=11678.76
       1 3965.85 4510.91
Encroach Node=11195.29
       1 3813.76    4650
Encroach Node=11127.97
       1    3780    4650
Encroach Node=11095.64
       1    3460    4690
Encroach Node=10966.89
       1    3520    4780
Encroach Node=10863.14
       1  3488.2    4695
Encroach Node=10083.36
       1 3263.96    4425
Encroach Node=9089.908
       1 3116.92 4240.43
Encroach Node=7988.222
       1 2903.58 3975.11
Encroach Node=6900.337
       1 3176.06 3802.06
Encroach Node=5905.715
       1  3303.3 3782.19
Encroach Node=4819.394
       1 3052.34 3590.03
Encroach Node=3818.178
       1 2940.42 3338.65
Encroach Node=3757.805
       1  2850.4  3278.6
Encroach Node=2756.127
       1  2900.5  3529.5
Encroach Node=1642.161
       1 3190.98  3301.8
Encroach Node=1091.952
       1 3346.88 3431.14
Encroach Node=554.192
       1 3109.92 3208.44
Encroach Node=354.000
       1 3103.45 3203.36
Encroach Node=65.909
       1 3128.98 3221.79
Computation Interval=1HOUR
Output Interval=1HOUR
Run HTab= 0
Run UNet= 0
Run PostProcess= 0
UNET Theta= 1
UNET ZTol= 0.02
UNET ZSATol= 0.1
UNET MxIter= 20
UNET MaxInSteps= 20
UNET DtIC= 0
UNET DtMin= 0
UNET MaxCRTS= 20
UNET WFStab= 2
UNET SFStab= 1
UNET WFX= 1
UNET SFX= 1
UNET Convert EG Bridges=-1
UNET Use Existing IB Tables=-1
Instantaneous Interval=1HOUR
DSS File=dss
Write IC File= 0
Write Velocity= 0
Write Detailed= 0

--- Q122-00-00.p01 (plan) ---

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Plan Title=FEMA Effective June 2007
Short Identifier=FEMAeff0607
Geom File=g01
Flow File=f01
Encroach Param= 0 ,0,0, 2

--- Q122-00-00.f02 (steady flow) ---

Flow Title=Floodway
Version=Version 3.0.1  Mar 2001
Number of Profiles= 2
Profile Names=1PCT_100yr,1PCTFloodway_100yrFW
River Rch & RM=Q122-00-00,Q122-00-00_0001 ,19678.05
     605     605
River Rch & RM=Q122-00-00,Q122-00-00_0001 ,19531.76
     625     625
River Rch & RM=Q122-00-00,Q122-00-00_0001 ,19353.98
     702     702
River Rch & RM=Q122-00-00,Q122-00-00_0001 ,18736.11
     849     849
River Rch & RM=Q122-00-00,Q122-00-00_0001 ,17715.47
     863     863
River Rch & RM=Q122-00-00,Q122-00-00_0001 ,17633.30
    1022    1022
River Rch & RM=Q122-00-00,Q122-00-00_0001 ,16727.14
    1239    1239
River Rch & RM=Q122-00-00,Q122-00-00_0001 ,15696.69
    1415    1415
River Rch & RM=Q122-00-00,Q122-00-00_0001 ,14987.37
    1794    1794
River Rch & RM=Q122-00-00,Q122-00-00_0001 ,14696.12
    1857    1857
River Rch & RM=Q122-00-00,Q122-00-00_0001 ,13659.84
    1919    1919
River Rch & RM=Q122-00-00,Q122-00-00_0001 ,12683.52
    1985    1985
River Rch & RM=Q122-00-00,Q122-00-00_0001 ,11678.76
    2033    2033
River Rch & RM=Q122-00-00,Q122-00-00_0001 ,10863.14
    2094    2094
River Rch & RM=Q122-00-00,Q122-00-00_0001 ,10083.36
    2165    2165
River Rch & RM=Q122-00-00,Q122-00-00_0001 ,9089.908
    2247    2247
River Rch & RM=Q122-00-00,Q122-00-00_0001 ,7988.222
    2330    2330
River Rch & RM=Q122-00-00,Q122-00-00_0001 ,6900.337
    2409    2409
River Rch & RM=Q122-00-00,Q122-00-00_0001 ,5905.715
    2499    2499
River Rch & RM=Q122-00-00,Q122-00-00_0001 ,4819.394
    2584    2584
River Rch & RM=Q122-00-00,Q122-00-00_0001 ,3818.178
    3898    3898
River Rch & RM=Q122-00-00,Q122-00-00_0001 ,3757.805
    3961    3961
River Rch & RM=Q122-00-00,Q122-00-00_0001 ,1642.161
    4008    4008
Boundary for River Rch & Prof#=Q122-00-00,Q122-00-00_0001 , 1
Up Type= 0
Dn Type= 3
Dn Slope=.0066
Boundary for River Rch & Prof#=Q122-00-00,Q122-00-00_0001 , 2
Up Type= 0
Dn Type= 3
Dn Slope=.0066
DSS Import GetInterval= 0
DSS Import GetPeak= 0
DSS Import FillOption= 0

--- Q122-00-00.f01 (steady flow) ---

Flow Title=FEMA Effective June 2007
Version=Version 3.0.1  Mar 2001
Number of Profiles= 4
Profile Names=10PCT_10yr,2PCT_50yr,1PCT_100yr,0.2PCT_500yr
River Rch & RM=Q122-00-00,Q122-00-00_0001 ,19678.05
     341     515     605     871
River Rch & RM=Q122-00-00,Q122-00-00_0001 ,19531.76
     353     532     625     901
River Rch & RM=Q122-00-00,Q122-00-00_0001 ,19353.98
     396     597     702    1011
River Rch & RM=Q122-00-00,Q122-00-00_0001 ,18736.11
     479     723     849    1224
River Rch & RM=Q122-00-00,Q122-00-00_0001 ,17715.47
     487     734     863    1243
River Rch & RM=Q122-00-00,Q122-00-00_0001 ,17633.30
     576     869    1022    1472
River Rch & RM=Q122-00-00,Q122-00-00_0001 ,16727.14
     699    1054    1239    1785
River Rch & RM=Q122-00-00,Q122-00-00_0001 ,15696.69
     798    1204    1415    2038
River Rch & RM=Q122-00-00,Q122-00-00_0001 ,14987.37
    1012    1526    1794    2584
River Rch & RM=Q122-00-00,Q122-00-00_0001 ,14696.12
    1045    1578    1857    2687
River Rch & RM=Q122-00-00,Q122-00-00_0001 ,13659.84
    1077    1628    1919    2787
River Rch & RM=Q122-00-00,Q122-00-00_0001 ,12683.52
    1111    1681    1985    2893
River Rch & RM=Q122-00-00,Q122-00-00_0001 ,11678.76
    1136    1719    2033    2972
River Rch & RM=Q122-00-00,Q122-00-00_0001 ,10863.14
    1167    1769    2094    3072
River Rch & RM=Q122-00-00,Q122-00-00_0001 ,10083.36
    1204    1826    2165    3188
River Rch & RM=Q122-00-00,Q122-00-00_0001 ,9089.908
    1246    1891    2247    3322
River Rch & RM=Q122-00-00,Q122-00-00_0001 ,7988.222
    1288    1958    2330    3460
River Rch & RM=Q122-00-00,Q122-00-00_0001 ,6900.337
    1329    2021    2409    3592
River Rch & RM=Q122-00-00,Q122-00-00_0001 ,5905.715
    1374    2093    2499    3741
River Rch & RM=Q122-00-00,Q122-00-00_0001 ,4819.394
    1418    2161    2584    3884
River Rch & RM=Q122-00-00,Q122-00-00_0001 ,3818.178
    2137    3245    3898    5965
River Rch & RM=Q122-00-00,Q122-00-00_0001 ,3757.805
    2190    3314    3961    5965
River Rch & RM=Q122-00-00,Q122-00-00_0001 ,1642.161
    2230    3367    4008    5965
Boundary for River Rch & Prof#=Q122-00-00,Q122-00-00_0001 , 1
Up Type= 0
Dn Type= 3
Dn Slope=.0066
Boundary for River Rch & Prof#=Q122-00-00,Q122-00-00_0001 , 2
Up Type= 0
Dn Type= 3
Dn Slope=.0066
Boundary for River Rch & Prof#=Q122-00-00,Q122-00-00_0001 , 3
Up Type= 0
Dn Type= 3
Dn Slope=.0066
Boundary for River Rch & Prof#=Q122-00-00,Q122-00-00_0001 , 4
Up Type= 0
Dn Type= 3
Dn Slope=.0066
DSS Import GetInterval= 0
DSS Import GetPeak= 0
DSS Import FillOption= 0

--- Q122-00-00.g01 (geometry) ---

Geom Title=Q122-00-00 June 2007
Version=Version 3.0.1  Mar 2001

River Reach=Q122-00-00            ,Q122-00-00_0001
Reach XY= 30
     3225934.158    13887594.253     3226297.338    13886777.593
     3227062.399    13885914.295     3229118.437    13884549.888
     3232960.608    13883373.024     3234426.229    13883389.894
     3235699.345     13883345.24     3236112.141    13883590.337
     3236395.937    13883666.744     3237129.244    13883694.528
      3237672.03     13883807.65     3237908.197    13883743.151
     3238358.699     13883772.92      3238696.08    13883857.265
     3238936.216    13883965.425     3239146.583    13883966.418
      3239413.51    13884061.678     3239787.606    13884138.085
     3240273.831    13884342.498     3240378.022    13884294.868
     3241446.725    13884228.384     3241566.793    13884158.923
     3241645.185    13884162.892     3242042.103    13884315.706
     3242416.199    13884376.236     3242768.464    13884379.213
     3243001.654    13884478.443     3243194.159    13884651.102
     3243315.219    13884715.601     3243707.576    13884695.088

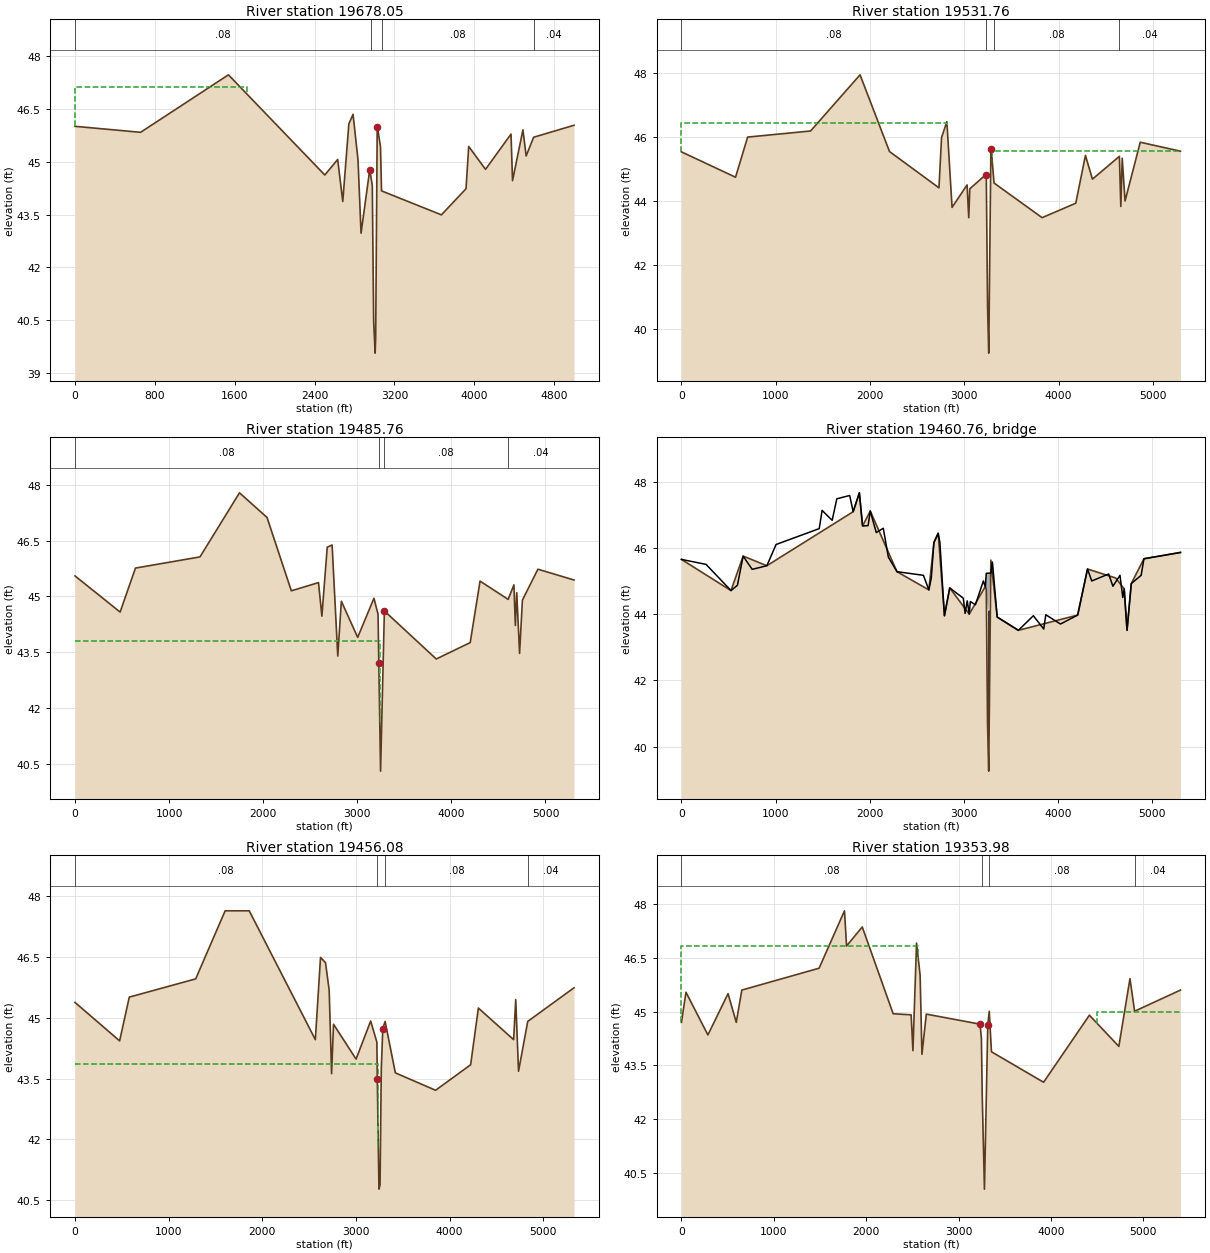
Type RM Length L Ch R = 1 ,19678.05,146.3,146.3,146.3
BEGIN DESCRIPTION:
S
END DESCRIPTION:
XS GIS Cut Line= 6
     3227903.815    13889794.814     3226320.457    13887767.354
     3225989.525    13887580.731     3225884.158    13887559.157
     3224874.998    13887505.922     3223949.465    13887569.654
#Sta/Elev= 30
       0      46  657.22   45.83 1536.93   47.46 2502.16   44.62 2631.37   45.06
  2682.1   43.87 2743.17   46.07 2785.28   46.34 2834.78   45.05 2865.32   42.97
  2952.4   44.77 2963.81   44.57 2977.94   44.32 2991.55   40.47 3006.37   39.57
 3011.77   39.99 3027.12   46.02 3029.68   45.97 3059.95   45.42 3070.49   44.17
 3670.14   43.49 3916.57   44.23 3943.65   45.43 4111.88   44.78 4367.48   45.78
 4382.52   44.46 4486.75    45.9 4518.91   45.16  4593.7   45.69 4998.24   46.03
#Mann= 4 ,-1 , 0
       0     .08       0 2963.81     .04       0 3070.49     .08       0
  4593.7     .04       0
#XS Ineff= 2 , 0
       0 1725.08   47.12 3027.12       0   46.02
Permanent Ineff=
       F       F
Bank Sta=2952.4,3029.68
XS Rating Curve= 0
Exp/Cntr=.3,.1

Type RM Length L Ch R = 1 ,19531.76,45.99,45.99,45.99
XS GIS Cut Line= 6
     3228225.525    13889781.409     3226540.253    13887771.487
     3226053.087    13887459.225     3225964.909    13887420.649
     3225337.758    13887344.472     3223976.275    13887368.586
#Sta/Elev= 30
       0   45.53  573.55   44.74  701.83   45.99 1369.08   46.18 1893.82   47.93
 2206.03   45.54 2730.41   44.41  2758.2   45.98 2814.42   46.47 2869.39    43.8
 3028.61    44.5 3046.43   43.48 3057.43   44.38 3224.32   44.81 3232.51   44.74
 3245.93   40.71 3258.46   39.26 3281.18   45.63 3284.64   45.62 3314.45   44.56
  3824.1   43.48 4181.29   43.93  4283.7   45.42 4357.99   44.68 4643.76   45.39
 4658.76   43.83 4673.76   45.33 4703.77      44 4865.02   45.83 5291.32   45.55
#Mann= 4 ,-1 , 0
       0     .08       0 3224.32     .04       0 3314.45     .08       0
 4643.76     .04       0
#XS Ineff= 2 , 0
       0 2816.62   46.42 3297.86       0   45.57
Permanent Ineff=
       F       F
Bank Sta=3224.32,3284.64
XS Rating Curve= 0
Exp/Cntr=.5,.3

Type RM Length L Ch R = 1 ,19485.76,29.68,29.68,29.68
XS GIS Cut Line= 6
     3228243.393    13889743.463      3226553.39    13887723.788
     3226068.076    13887415.583     3225979.898    13887377.007
     3225362.011    13887308.121     3223985.418     13887307.36
#Sta/Elev= 30
       0   45.55  479.58   44.58  642.56   45.76 1328.25   46.06 1748.08   47.78
 2040.66   47.12 2299.02   45.15 2587.84   45.37 2623.66   44.47 2680.64   46.32
 2732.44   46.38 2792.56    43.4  2830.7   44.87 3004.18    43.9 3177.03   44.95
 3220.55   44.52  3228.7    43.2 3247.43   40.31 3287.88   44.61 3839.09   43.32
  4199.8   43.76 4304.62   45.41 4603.11   44.92 4664.62   45.31 4679.62   44.22
 4694.62    45.1 4724.62   43.47 4754.62    44.9 4919.62   45.73 5302.94   45.44
#Mann= 4 ,-1 , 0
       0     .08       0  3228.7     .04       0 3287.88     .08       0
 4603.11     .04       0
#XS Ineff= 2 , 0
       0 3239.33    43.8 3285.05       0    43.8
Permanent Ineff=
       F       F
Bank Sta=3228.7,3287.88
XS Rating Curve= 0
Exp/Cntr=.5,.3

Type RM Length L Ch R = 3 ,19460.76,,,
BEGIN DESCRIPTION:
Wooden Access Bridge Most u/s of FM 1942 Bridge
END DESCRIPTION:
Bridge Culvert--1,0,-1,-1, 0
Deck Dist Width WeirC Skew NumUp NumDn MinLoCord MaxHiCord MaxSubmerge Is_Ogee
6,17,2.6,0, 60, 60, , , .95, 0, 0,0,,
       0  261.21  526.44   594.8  655.43  751.27  907.74 1005.26 1464.27  1494.5
 1601.72 1650.97 1787.88 1824.72 1890.56 1924.79 1983.46 2006.36 2070.25 2144.79
 2198.61 2290.22 2571.32  2628.9 2654.91 2682.89 2728.38 2746.15 2794.81 2850.77
 2994.92 3014.12 3036.74 3058.47 3069.34 3123.68 3208.38 3229.49 3238.83 3287.91
 3304.63 3355.63 3580.24 3739.69 3849.61 3871.63 4027.78 4210.42 4315.08 4360.08
 4540.08 4585.08 4660.08 4690.08 4705.08 4735.08 4780.08 4885.08  4914.8 5302.94
   45.65    45.5   44.71   44.87   45.75   45.35   45.46    46.1   46.58   47.13
   46.83   47.48   47.58   47.09   47.66   46.66   46.67   47.11   46.46   46.59
   45.72   45.28   45.17   44.73   45.09   46.16   46.44   46.17   43.95   44.79
   44.48   44.02    44.4      44   44.38   44.28      45   44.82   45.23   45.24
   45.57   43.91   43.51   43.95   43.55   43.98    43.7   43.97   45.36      45
   45.21   44.84   45.17    44.5   44.76   43.51   44.92   45.17   45.67   45.86
   45.65    45.5   44.71   44.87   45.75   45.35   45.46    46.1   46.58   47.13
   46.83   47.48   47.58   47.09   47.66   46.66   46.67   47.11   46.46   46.59
   45.72   45.28   45.17   44.73   45.09   46.16   46.44   46.17   43.95   44.79
   44.48   44.02    44.4      44   44.38   44.28      45   44.82   44.13   44.14
   45.57   43.91   43.51   43.95   43.55   43.98    43.7   43.97   45.36      45
   45.21   44.84   45.17    44.5   44.76   43.51   44.92   45.17   45.67   45.86
       0  275.08  356.77   438.6   529.4  577.49  679.34  715.84  833.86 1071.02
  1423.8  1482.1 1503.39 1620.45 1643.66 1759.65 1841.42  1982.3 2078.09 2171.06
  2203.2 2393.77 2432.34 2578.29 2623.35 2677.52 2726.58  2740.5 2746.71 2791.42
 3008.93 3122.82 3207.15 3238.04 3238.83 3287.91 3291.28  3303.4 3347.07 3527.94
 3830.83 3861.07 3936.66  4054.4 4212.34 4251.71 4281.71 4346.25 4405.76 4446.72
 4596.72 4671.73 4686.73 4716.73 4731.73 4746.73 4791.73 5002.59 5046.74 5313.35
   45.47   45.35   44.88   45.25   44.72   45.47   45.12   45.55   45.43   46.22
   46.29   46.95   46.66   47.45    47.1   47.55   47.06   47.15   46.35   46.69
   45.48   45.44   45.01    44.7   46.31   46.42   45.45   44.22   44.12   44.81
   44.16   44.36      45   44.74   45.23   45.24   45.62   45.57    44.1   43.48
   43.87   43.35   43.99   43.66    44.3   44.09    44.8   45.27   44.88   45.23
   44.79   45.08   44.72   45.29   44.34   44.08   44.83   45.34   45.78   45.88
   45.47   45.35   44.88   45.25   44.72   45.47   45.12   45.55   45.43   46.22
   46.29   46.95   46.66   47.45    47.1   47.55   47.06   47.15   46.35   46.69
   45.48   45.44   45.01    44.7   46.31   46.42   45.45   44.22   44.12   44.81
   44.16   44.36      45   44.74   44.13   44.14   45.62   45.57    44.1   43.48
   43.87   43.35   43.99   43.66    44.3   44.09    44.8   45.27   44.88   45.23
   44.79   45.08   44.72   45.29   44.34   44.08   44.83   45.34   45.78   45.88
Pier Skew, UpSta & Num, DnSta & Num=  ,3258.75, 2 ,3258.75, 2 , 0 , 0 , 0 ,,
       1       1
   39.45   44.11
       1       1
   39.45   44.11
Pier Skew, UpSta & Num, DnSta & Num=  ,3271.69, 2 ,3271.69, 2 , 0 , 0 , 0 ,,
       1       1
   39.35   44.14
       1       1
   39.35   44.14
BR Coef=-1 , 1 , 1 ,1.25, 0 ,,.34,.8,0,2,0,
WSPro=,,,, 1 ,,,, 0 ,,,, 0 ,,,,-1 ,-1 ,-1 , 0 , 0 , 0 , 0 , 0
BR U #Sta/Elev= 30
       0   45.65  526.44   44.71  655.43   45.75  907.74   45.46 1824.72   47.09
 1890.56   47.66 1924.79   46.66 2006.36   47.11 2290.22   45.28  2628.9   44.73
 2682.89   46.16 2728.38   46.44 2794.81   43.95 2850.77   44.79 3058.47      44
  3228.7   44.83 3239.28   44.74  3252.7   40.71 3265.23   39.26 3287.95   45.63
 3355.63   43.91 3580.24   43.51 4210.42   43.97 4315.08   45.36 4614.64   45.09
 4705.08   44.76 4735.08   43.51 4780.08   44.92  4914.8   45.67 5302.94   45.86
BR U #Mann= 5
       0     .04  3228.7     .04 3239.28    .035 3287.95     .04 4614.64     .04
BR D #Sta/Elev= 30
       0   45.47   529.4   44.72  577.49   45.47  1423.8   46.29 1759.65   47.55
 2171.06   46.69  2203.2   45.48 2578.29    44.7 2623.35   46.31 2677.52   46.42
 2726.58   45.45 2746.71   44.12 2791.42   44.81 3008.93   44.16 3207.15      45
 3238.04   44.74 3251.47   40.71 3263.99   39.26 3286.72   45.63 3316.83   44.95
 3347.07    44.1 3504.61   43.51 3861.07   43.35 4251.71   44.09 4346.25   45.27
 4686.73   44.72 4716.73   45.29 4746.73   44.08 4821.73   44.96 5328.49   45.85
BR D #Mann= 5
       0     .04 3207.15     .04 3238.04    .035 3316.83     .04 4821.73     .04
BC Design=,, 0 ,, 0 ,,,,,,

Type RM Length L Ch R = 1 ,19456.08,102.1,102.1,102.1
XS GIS Cut Line= 6
     3228271.155     13889698.35     3226570.741    13887692.556
     3226079.781    13887388.313     3225991.603    13887349.736
     3225357.629     13887270.14     3223971.537    13887258.777
#Sta/Elev= 30
       0   45.38  476.68   44.43  579.85   45.51 1288.85   45.96 1603.32   47.64
  1860.7   47.64 2566.57   44.46 2621.77   46.49 2675.22   46.36 2714.28   45.68
 2739.94   43.62 2760.65   44.84 3001.43   43.98 3157.34   44.92 3223.42    44.4
 3228.16   43.49 3245.76   40.77 3257.41   40.87 3270.69   43.74 3286.61   44.73
 3311.44   44.91 3420.98   43.64 3850.53   43.21 4224.81   43.84 4307.47   45.24
 4684.04   44.46 4706.27   45.45 4736.27   43.68 4834.46   44.91 5328.49   45.74
#Mann= 4 ,-1 , 0
       0     .08       0 3228.16     .04       0 3311.44     .08       0
 4834.46     .04       0
#XS Ineff= 2 , 0
       0 3239.33   43.85 3285.05       0   43.85
Permanent Ineff=
       F       F
Bank Sta=3228.16,3286.61
XS Rating Curve= 0
Exp/Cntr=.5,.3

Type RM Length L Ch R = 1 ,19353.98,617.87,617.87,617.87
XS GIS Cut Line= 6
     3228301.567     13889656.14     3226601.973     13887609.27
     3226120.747    13887294.812      3226032.57    13887256.236
     3225340.099    13887170.805     3223968.067     13887161.61
#Sta/Elev= 30
       0    44.7   48.92   45.54   286.2   44.35  504.29    45.5   593.3    44.7
  653.32    45.6 1489.86   46.21 1764.64   47.81 1787.15   46.83  1957.2   47.36
 2291.57   44.94 2486.03   44.91 2505.53   43.91 2544.52   46.91 2583.51   46.01
 2603.01   43.81 2650.51   44.93  3231.8   44.65 3246.71   44.26 3255.96   42.62
 3279.65   40.05 3315.65   44.63 3331.61   45.01 3355.53   43.88 3919.87   43.03
  4415.7    44.9 4734.42   44.03 4854.83   45.92    4905   45.01  5401.4    45.6
#Mann= 4 ,-1 , 0
       0     .08       0 3255.96     .04       0 3331.61     .08       0
    4905     .04       0
#XS Ineff= 2 , 0
       0 2565.71   46.84 4501.14       0   44.99
Permanent Ineff=
       F       F
Bank Sta=3231.8,3315.65
XS Rating Curve= 0
Exp/Cntr=.3,.1

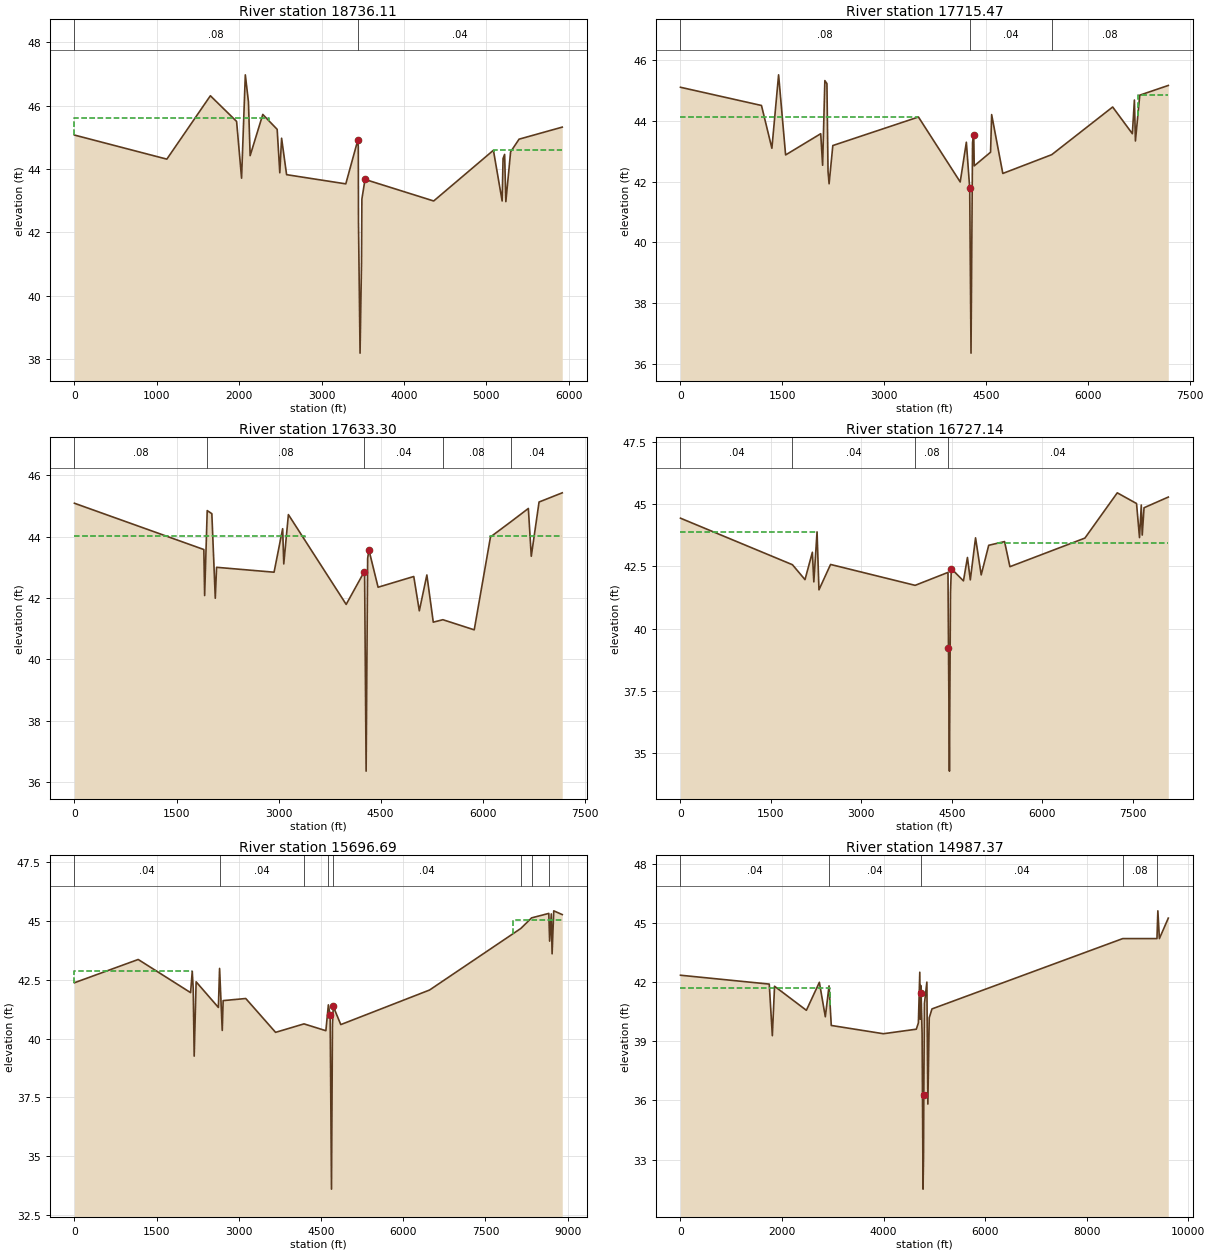
Type RM Length L Ch R = 1 ,18736.11,1020.64,1020.64,1020.64
BEGIN DESCRIPTION:
R
END DESCRIPTION:
XS GIS Cut Line= 6
     3228278.276    13889532.664     3228015.293    13888724.932
     3227507.296    13887926.269     3226387.757    13886763.992
     3226302.927    13886682.392     3223909.252    13886725.166
#Sta/Elev= 30
       0   45.07 1121.72   44.31 1650.25   46.31 1968.58    45.5 2028.93   43.71
 2074.36   46.97 2112.24   46.12 2133.06   44.42 2286.51   45.72 2460.93   45.25
 2493.03   43.88 2514.65   44.97 2575.41   43.82 3294.04   43.53 3440.05   44.91
 3445.86    44.7 3447.98   42.34 3467.24   38.19  3484.9   41.05 3489.38   43.05
 3527.47   43.67 4361.15   42.99 5086.05   44.59 5191.93   42.99 5203.11   44.33
 5221.94   44.46 5236.94   42.97 5294.76   44.54 5397.62   44.94 5921.53   45.32
#Mann= 2 ,-1 , 0
       0     .08       0 3440.05     .04       0
#XS Ineff= 2 , 0
       0 2364.18    45.6    5090       0    44.6
Permanent Ineff=
       F       F
Bank Sta=3440.05,3527.47
XS Rating Curve= 0
Exp/Cntr=.3,.1

Type RM Length L Ch R = 1 ,17715.47,82.17,82.17,82.17
BEGIN DESCRIPTION:
Q
END DESCRIPTION:
XS GIS Cut Line= 6
     3228868.945    13889781.409     3228105.915    13887562.266
     3227059.079    13886004.308     3227023.079    13885960.968
     3226999.204    13885932.223     3224140.252    13886046.231
#Sta/Elev= 30
       0   45.11 1191.76   44.51 1344.94    43.1  1443.7   45.52  1546.8   42.88
 2063.64   43.58 2091.56   42.54 2124.55   45.33 2155.01   45.23 2171.13   42.34
 2186.73   41.93 2241.84   43.19 3501.75   44.13 4116.36   41.99 4206.65    43.3
  4255.9   41.79 4275.26   36.35 4297.79   43.29 4314.83   43.55 4322.83   42.52
 4563.02   42.97  4578.9   44.21 4743.17   42.27 5463.74   42.89 6359.92   44.46
 6649.68   43.58 6679.71   44.69 6694.72   43.34 6758.77   44.85 7178.59   45.17
#Mann= 3 ,-1 , 0
       0     .08       0  4255.9     .04       0 5463.74     .08       0
#XS Ineff= 2 , 0
       0 3490.13   44.13 6730.12       0   44.85
Permanent Ineff=
       F       F
Bank Sta=4255.9,4314.83
XS Rating Curve= 0
Exp/Cntr=.3,.1

Type RM Length L Ch R = 1 ,17633.30,906.16,906.16,906.16
BEGIN DESCRIPTION:
P
END DESCRIPTION:
XS GIS Cut Line= 6
     3229114.371     13889608.27     3228387.119    13887542.873
     3227113.398    13885942.686     3227066.027    13885885.653
     3227053.524    13885870.601     3224213.589     13885842.52
#Sta/Elev= 30
       0   45.09 1901.74   43.58  1913.5   42.08 1951.38   44.85 2019.35   44.75
 2069.98   41.99 2088.96      43 2933.76   42.84    3060   44.26 3076.32   43.11
 3144.36   44.72 3993.53   41.79 4255.06   42.84 4264.28   42.77 4286.54   36.35
 4309.06   43.29 4327.25   43.57 4462.33   42.35 4986.68    42.7 5068.35   41.58
 5179.12   42.75 5273.47   41.21 5414.83   41.29  5875.3   40.96 6114.07   43.99
 6410.04   44.48 6670.77   44.92 6713.54   43.36 6827.95   45.13 7168.71   45.43
#Mann= 5 ,-1 , 0
       0     .08       0 1951.38     .08       0 4255.06     .04       0
 5414.83     .08       0 6410.04     .04       0
#XS Ineff= 2 , 0
       0 3381.49   44.02 6113.79       0   44.01
Permanent Ineff=
       F       F
Bank Sta=4255.06,4327.25
XS Rating Curve= 0
Exp/Cntr=.3,.1

Type RM Length L Ch R = 1 ,16727.14,1030.45,1030.45,1030.45
BEGIN DESCRIPTION:
O
END DESCRIPTION:
XS GIS Cut Line= 6
     3229725.263    13889356.155     3229066.463    13886989.713
      3227866.62    13885448.765     3227850.735    13885425.262
     3227824.749    13885386.818     3224221.737    13885182.493
#Sta/Elev= 30
       0   44.44 1857.03   42.57 2065.82   41.97  2187.8   43.07 2211.98   41.88
 2265.65   43.89 2297.23   41.56 2489.65   42.58  3892.7   41.74 4437.79   42.26
 4446.21   39.24 4461.64   34.27  4479.3   41.45 4493.55   42.41 4694.61   41.92
 4760.64   42.86 4808.24   41.96 4895.02   43.65 4988.91   42.16 5113.53   43.35
 5376.63    43.5 5465.11   42.49 6709.37   43.64 7246.54   45.46    7566   45.03
 7615.22   43.66 7644.64   44.97 7660.29   43.76 7690.34   44.86 8092.99   45.29
#Mann= 4 ,-1 , 0
       0     .04       0 1857.03     .04       0  3892.7     .08       0
 4437.79     .04       0
#XS Ineff= 2 , 0
       0  2266.3    43.9 5258.86       0   43.44
Permanent Ineff=
       F       F
Bank Sta=4446.21,4493.55
XS Rating Curve= 0
Exp/Cntr=.3,.1

Type RM Length L Ch R = 1 ,15696.69,709.32,709.32,709.32
BEGIN DESCRIPTION:
N
END DESCRIPTION:
XS GIS Cut Line= 6
     3230316.762    13889123.435     3230045.254    13887009.554
     3228724.776    13884883.376     3228700.425    13884843.984
      3228683.43    13884816.489     3224498.785    13884620.249
#Sta/Elev= 30
       0   42.38 1163.81   43.37 2119.86   41.96 2150.14   42.87  2167.8   42.11
 2185.45   39.26 2220.77   42.42 2626.93   41.33 2648.69   42.99 2697.52   40.35
 2714.05   41.62 3126.45   41.71 3670.89   40.27 4189.45   40.63 4588.39   40.34
  4634.1   41.44 4666.33   40.99 4691.09    33.6 4708.74   40.58 4723.66   41.37
 4860.75    40.6 6480.21   42.07  8146.2   44.69 8342.42   45.14 8656.76   45.33
 8671.78   44.15 8701.81   45.31 8716.83   43.61 8746.86   45.44 8901.98   45.28
#Mann= 8 ,-1 , 0
       0     .04       0 2648.69     .04       0 4189.45     .08       0
  4634.1     .04       0 4723.66     .04       0  8146.2     .04       0
 8342.42     .08       0 8656.76     .04       0
#XS Ineff= 2 , 0
       0 2150.14   42.88  7996.9       0   45.05
Permanent Ineff=
       F       F
Bank Sta=4666.33,4723.66
XS Rating Curve= 0
Exp/Cntr=.3,.1

Type RM Length L Ch R = 1 ,14987.37,291.25,291.25,291.25
BEGIN DESCRIPTION:
M
END DESCRIPTION:
XS GIS Cut Line= 6
       3231080.7    13888789.471     3230642.126     13886331.44
     3229321.079    13884542.099      3229305.39    13884478.079
     3229294.811    13884434.907     3224523.231    13884220.973
#Sta/Elev= 30
       0   42.36 1748.06   41.91 1809.09   39.29 1852.45    41.8 2479.52   40.58
 2735.32      42 2852.54   40.25 2925.48   41.82 2969.75   39.81 3996.23   39.39
 4644.58   39.62 4685.48   39.94 4713.05   42.51 4721.01   40.13 4731.78   41.84
 4739.21   41.45  4758.7   39.39 4777.37    31.5 4786.93   33.18 4792.54   36.26
 4804.32   40.92 4852.48   42.01 4872.07   35.82  4899.2    40.2 4953.21   40.65
 8709.94   44.22 9384.49   44.22 9402.04   45.63 9432.07   44.22 9607.75   45.26
#Mann= 5 ,-1 , 0
       0     .04       0 2925.48     .04       0 4731.78     .04       0
 8709.94     .08       0 9384.49     .04       0
#XS Ineff= 2 , 0
       0 2948.54   41.69 7151.06       0   42.24
Permanent Ineff=
       F       F
Bank Sta=4739.21,4792.54
XS Rating Curve= 0
Exp/Cntr=.3,.1

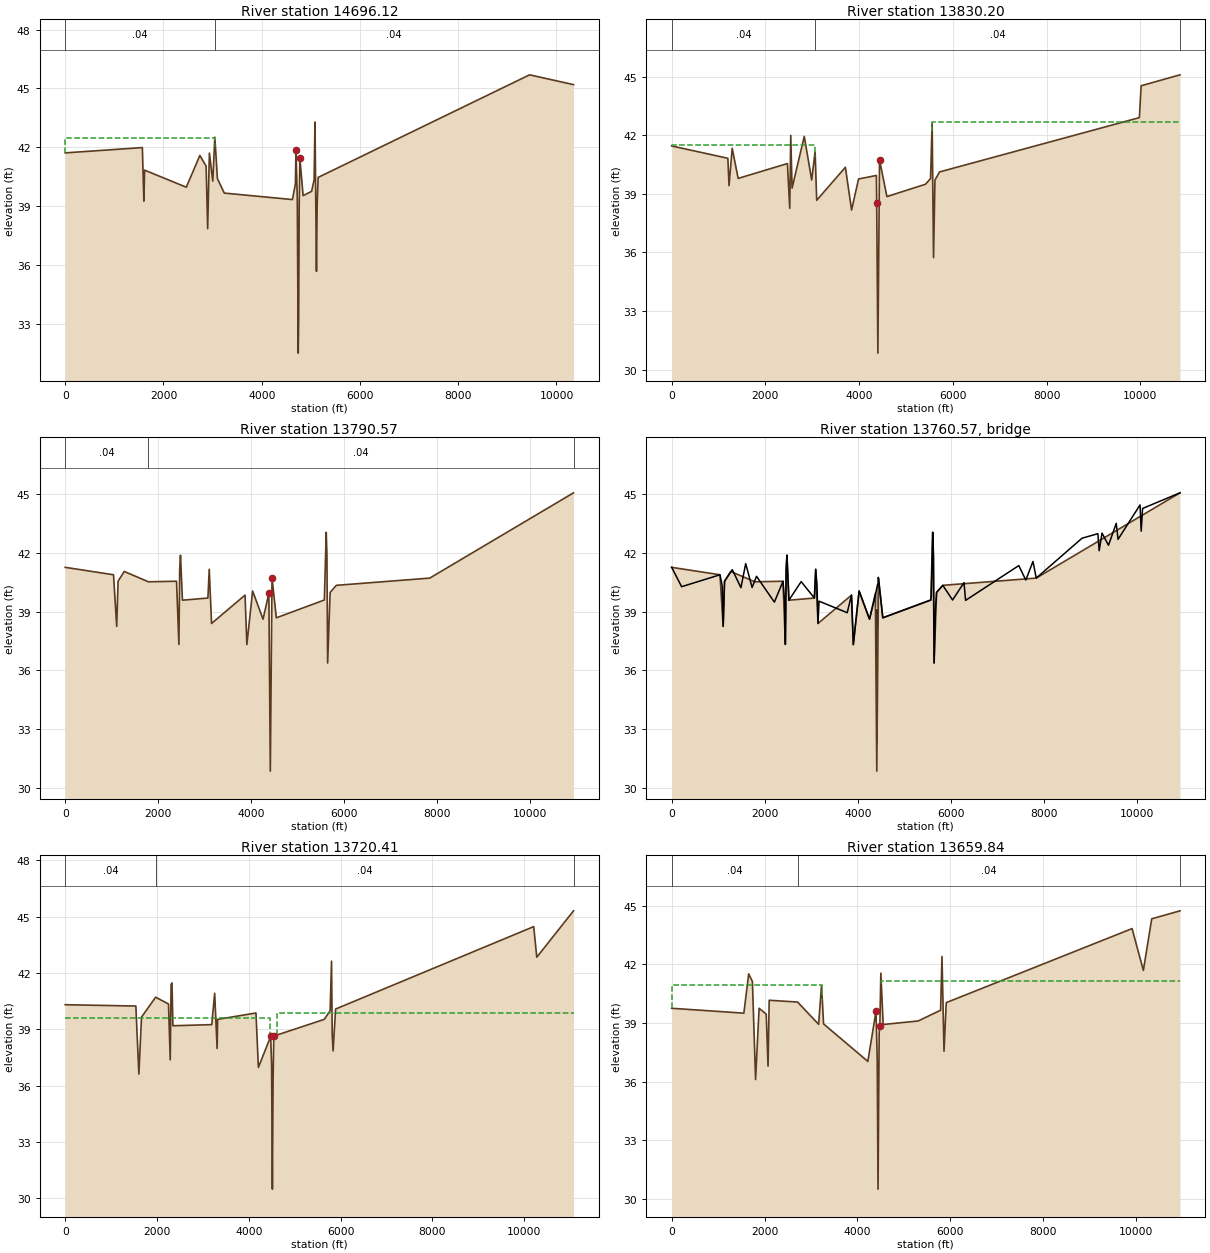
Type RM Length L Ch R = 1 ,14696.12,865.91,865.91,865.91
XS GIS Cut Line= 6
     3231509.646    13888601.807     3231170.071     13886611.99
     3230510.696     13885496.87     3229601.671    13884469.001
     3229575.403    13884361.809     3224041.961    13883930.175
#Sta/Elev= 30
       0   41.71 1570.69   41.98 1601.12   39.25 1616.34   40.83 2464.86   39.96
 2741.21   41.58 2868.32   41.03 2899.75   37.85  2934.6    41.7 3004.03   40.27
 3045.76   42.51 3098.28    40.4  3238.1   39.66 4624.91   39.33 4686.23   40.13
    4697   41.84 4723.92   39.39 4742.58    31.5 4752.15   33.18 4762.68   38.96
 4776.31   41.44 4842.59   39.53 5016.08   39.75 5066.54   40.34 5084.13   43.28
 5114.23   35.67 5128.43   39.12 5148.94   40.46 9452.47   45.6910346.85   45.19
#Mann= 2 ,-1 , 0
       0     .04       0 3045.76     .04       0
#XS Ineff= 2 , 0
       0 3058.52   42.46 7409.54       0   42.43
Permanent Ineff=
       F       F
Bank Sta=4697,4776.31
XS Rating Curve= 0
Exp/Cntr=.3,.1

Type RM Length L Ch R = 1 ,13830.20,39.63,39.63,39.63
BEGIN DESCRIPTION:
L
END DESCRIPTION:
XS GIS Cut Line= 6
     3232188.225    13888182.855     3231587.029     13886728.35
     3230431.159    13884204.322     3230416.327    13884160.277
     3230394.687     13884096.02     3224029.229    13883611.875
#Sta/Elev= 30
       0   41.45  1199.1   40.82 1224.08   39.42 1291.41   41.33 1419.39   39.79
 2470.08   40.55 2519.57   38.26 2541.31   41.99 2569.07   39.29 2829.54   41.94
 2988.01   39.71 3061.02   41.16 3094.87   38.67 3707.43   40.36 3839.42   38.17
  3987.9   39.76 4369.14   39.94 4375.03   38.53 4400.51   30.85 4436.11   40.73
 4593.37   38.86 5414.88   39.49 5524.43   39.78 5558.34   42.62 5588.43   35.74
 5618.51    39.7 5715.57   40.12 9981.08    42.9 10018.7   44.5310848.08   45.09
#Mann= 3 ,-1 , 0
       0     .04       0 3061.02     .04       010848.08     .04       0
#XS Ineff= 2 , 0
       0 3048.21    41.5  5552.6       0    42.7
Permanent Ineff=
       F       F
Bank Sta=4375.03,4436.11
XS Rating Curve= 0
Exp/Cntr=.5,.3

Type RM Length L Ch R = 1 ,13790.57,70.16,70.16,70.16
XS GIS Cut Line= 6
     3232515.488    13888042.253     3230469.022    13884192.585
     3230458.208    13884160.472      3230432.55    13884084.283
      3229588.53    13883881.859     3224016.497    13883459.091
#Sta/Elev= 30
       0   41.27 1038.82   40.89 1107.33   38.25 1136.76   40.56 1269.23   41.06
 1789.49   40.53 2393.85   40.56 2444.82   37.33  2461.8   41.17 2478.79   41.89
 2520.76   39.59  3068.7    39.7 3097.14   41.17 3146.79    38.4  3866.7   39.85
 3905.76   37.32 4030.21   40.06  4253.9   38.62 4378.99   39.94 4410.37   30.85
 4447.02   40.72 4539.93   38.69 5571.99    39.6 5612.62   43.06 5627.66    41.9
  5642.7   36.38 5696.17   39.99 5830.02   40.35    7839   40.7210930.09   45.08
#Mann= 3 ,-1 , 0
       0     .04       0 1789.49     .04       010930.09     .04       0
#XS Ineff= 2 , 0
       0 4372.99   39.39 4454.55       0   39.39
Permanent Ineff=
       F       F
Bank Sta=4378.99,4447.02
XS Rating Curve= 0
Exp/Cntr=.5,.3

Type RM Length L Ch R = 3 ,13760.57,,,
BEGIN DESCRIPTION:
Wooden Access Bridge Just u/s of FM 1942 Bridge
END DESCRIPTION:
Bridge Culvert--1,0,-1,-1, 0
Deck Dist Width WeirC Skew NumUp NumDn MinLoCord MaxHiCord MaxSubmerge Is_Ogee
30,17,2.6,0, 60, 60, , , .95, 0, 0,0,,
       0  213.82 1038.82  1085.8 1107.33 1136.76    1304  1489.1 1591.54 1729.37
 1824.82 2208.71 2393.85 2427.83 2444.82  2461.8 2478.79 2520.76 2784.35  3068.7
 3097.14 3124.33 3146.79 3168.94 3774.56  3866.7 3905.76 4030.21  4253.9 4359.81
  4427.8  4443.1 4443.61 4539.93 5571.99 5582.53 5612.62 5627.66  5642.7 5672.79
 5696.17 5830.02 6039.95 6285.55 6319.64 7463.64 7614.76 7768.92    7839 8824.04
 9163.84 9192.36 9253.05 9392.55 9559.28 9597.6410070.6910095.4610125.5510930.09
   41.27   40.28   40.89   40.33   38.25   40.56   41.15   40.23   41.46   40.24
   40.81   39.49   40.56   39.55   37.33   41.17   41.89   39.59   40.54    39.7
   41.17   40.37    38.4   39.54   38.95   39.85   37.32   40.06   38.62   39.64
    40.4    40.4   40.76   38.69    39.6   39.82   43.06    41.9   36.38    39.2
   39.99   40.35    39.6   40.49   39.58   41.36   40.62   41.57   40.72   42.76
   42.99   42.12   43.02    42.4   43.52    42.7   44.46   43.12   44.28   45.08
   41.27   40.28   40.89   40.33   38.25   40.56   41.15   40.23   41.46   40.24
   40.81   39.49   40.56   39.55   37.33   41.17   41.89   39.59   40.54    39.7
   41.17   40.37    38.4   39.54   38.95   39.85   37.32   40.06   38.62   39.64
   39.03    39.3   40.76   38.69    39.6   39.82   43.06    41.9   36.38    39.2
   39.99   40.35    39.6   40.49   39.58   41.36   40.62   41.57   40.72   42.76
   42.99   42.12   43.02    42.4   43.52    42.7   44.46   43.12   44.28   45.08
       0  814.24 1431.62 1539.49 1562.32 1605.17 1623.95 1662.61  1950.6 1970.49
 2037.86 2077.46 2132.22 2250.77 2269.61 2288.45 2307.29 2326.13 2346.68 2479.13
 2671.34 3085.66 3108.94 3192.74  3256.6 3288.07 3310.12 3320.83 4027.32 4156.47
 4209.33 4243.73 4282.73 4323.11 4348.49 4431.49 4470.63  4532.5 4599.38 4736.68
 5715.01 5772.48 5787.59 5802.69 5817.79 5836.61  5863.1 5891.26  7178.4  9752.5
 9775.8110177.8610207.9910223.0510253.1810274.8210358.6410678.6611064.8111075.55
   40.31   40.51   39.52   40.24   39.73   36.62   38.35   39.65   39.83   40.71
   40.28   40.99   40.06   40.35   39.56   37.38   41.39   41.47   39.19   39.97
   39.27   39.28   39.91   39.25   40.92   40.58   37.98   39.53   38.86   39.87
   36.97   38.77   39.53    38.3   39.11   38.89    40.4    40.4   39.94   38.65
   39.78   39.99   42.41   42.63   38.74   37.85   39.91   40.08   40.43   43.57
   42.92   43.74   44.47   43.43   44.12   42.84    44.4    44.2   45.35   45.31
   40.31   40.51   39.52   40.24   39.73   36.62   38.35   39.65   39.83   40.71
   40.28   40.99   40.06   40.35   39.56   37.38   41.39   41.47   39.19   39.97
   39.27   39.28   39.91   39.25   40.92   40.58   37.98   39.53   38.86   39.87
   36.97   38.77   39.53    38.3   39.11   38.89    39.3   39.03   39.94   38.65
   39.78   39.99   42.41   42.63   38.74   37.85   39.91   40.08   40.43   43.57
   42.92   43.74   44.47   43.43   44.12   42.84    44.4    44.2   45.35   45.31
Pier Skew, UpSta & Num, DnSta & Num=  ,4404.3, 2 ,4508.9, 2 , 0 , 0 , 0 ,,
       1       1
   31.63   39.14
       1       1
   31.63   39.14
Pier Skew, UpSta & Num, DnSta & Num=  ,4415.73, 2 ,4520.33, 2 , 0 , 0 , 0 ,,
       1       1
   31.13   39.04
       1       1
   31.13   39.04
BR Coef=-1 , 1 , 1 ,1.25, 0 ,,.34,.8,0,2,0,
WSPro=,,,, 1 ,,,, 0 ,,,, 0 ,,,,-1 ,-1 ,-1 , 0 , 0 , 0 , 0 , 0
BC Design=,, 0 ,, 0 ,,,,,,

Type RM Length L Ch R = 1 ,13720.41,60.57,60.57,60.57
XS GIS Cut Line= 6
     3232915.477    13887896.802     3232442.763    13886684.715
     3230502.639    13884074.079     3229689.843    13883763.661
     3226813.689    13883425.952     3224074.899    13883171.279
#Sta/Elev= 30
       0   40.31 1539.49   40.24 1605.17   36.62 1662.61   39.65 1970.49   40.71
 2250.77   40.35 2288.45   37.38 2307.29   41.39 2326.13   41.47 2346.68   39.19
 3192.74   39.25  3256.6   40.92 3310.12   37.98 3320.83   39.53 4156.47   39.87
 4209.33   36.97 4476.74   38.62 4497.16   37.12 4514.04   30.49 4529.55   36.36
 4544.85   38.64 5644.19   39.53 5772.48   39.99 5802.69   42.63 5817.79   38.74
 5836.61   37.85 5891.26   40.0810207.99   44.4710274.82   42.8411075.55   45.31
#Mann= 3 ,-1 , 0
       0     .04       0 1970.49     .04       011075.55     .04       0
#XS Ineff= 2 , 0
       0 4466.57    39.6 4605.46       0   39.89
Permanent Ineff=
       F       F
Bank Sta=4476.74,4544.85
XS Rating Curve= 0
Exp/Cntr=.5,.3

Type RM Length L Ch R = 1 ,13659.84,976.31,976.31,976.31
XS GIS Cut Line= 6
     3233121.532    13887690.748     3232636.564    13886539.379
      3230599.37    13884168.378     3230562.756    13884062.724
     3229698.627    13883633.828     3224244.065    13883002.113
#Sta/Elev= 30
       0   39.75 1553.82    39.5 1658.21   41.51 1738.31   41.12 1806.08    36.1
 1881.85   39.75 2034.95   39.45 2074.51   36.79 2099.38   40.16 2709.89   40.07
 3163.21   38.93 3226.89   40.94 3269.44   38.95 4222.86   37.03 4398.83    39.6
 4425.33   37.12 4442.21   30.49 4467.19   38.49 4481.66   38.86  4502.8   41.55
 4553.04   38.92  5306.6    39.1 5788.99   39.65 5819.19    42.4 5862.55   37.55
 5910.74   40.04 9911.36   43.8310154.32   41.6910334.17   44.3310942.88   44.74
#Mann= 3 ,-1 , 0
       0     .04       0 2709.89     .04       010942.88     .04       0
#XS Ineff= 2 , 0
       0 3243.97   40.95 4513.35       0   41.14
Permanent Ineff=
       F       F
Bank Sta=4398.83,4481.66
XS Rating Curve= 0
Exp/Cntr=.3,.1