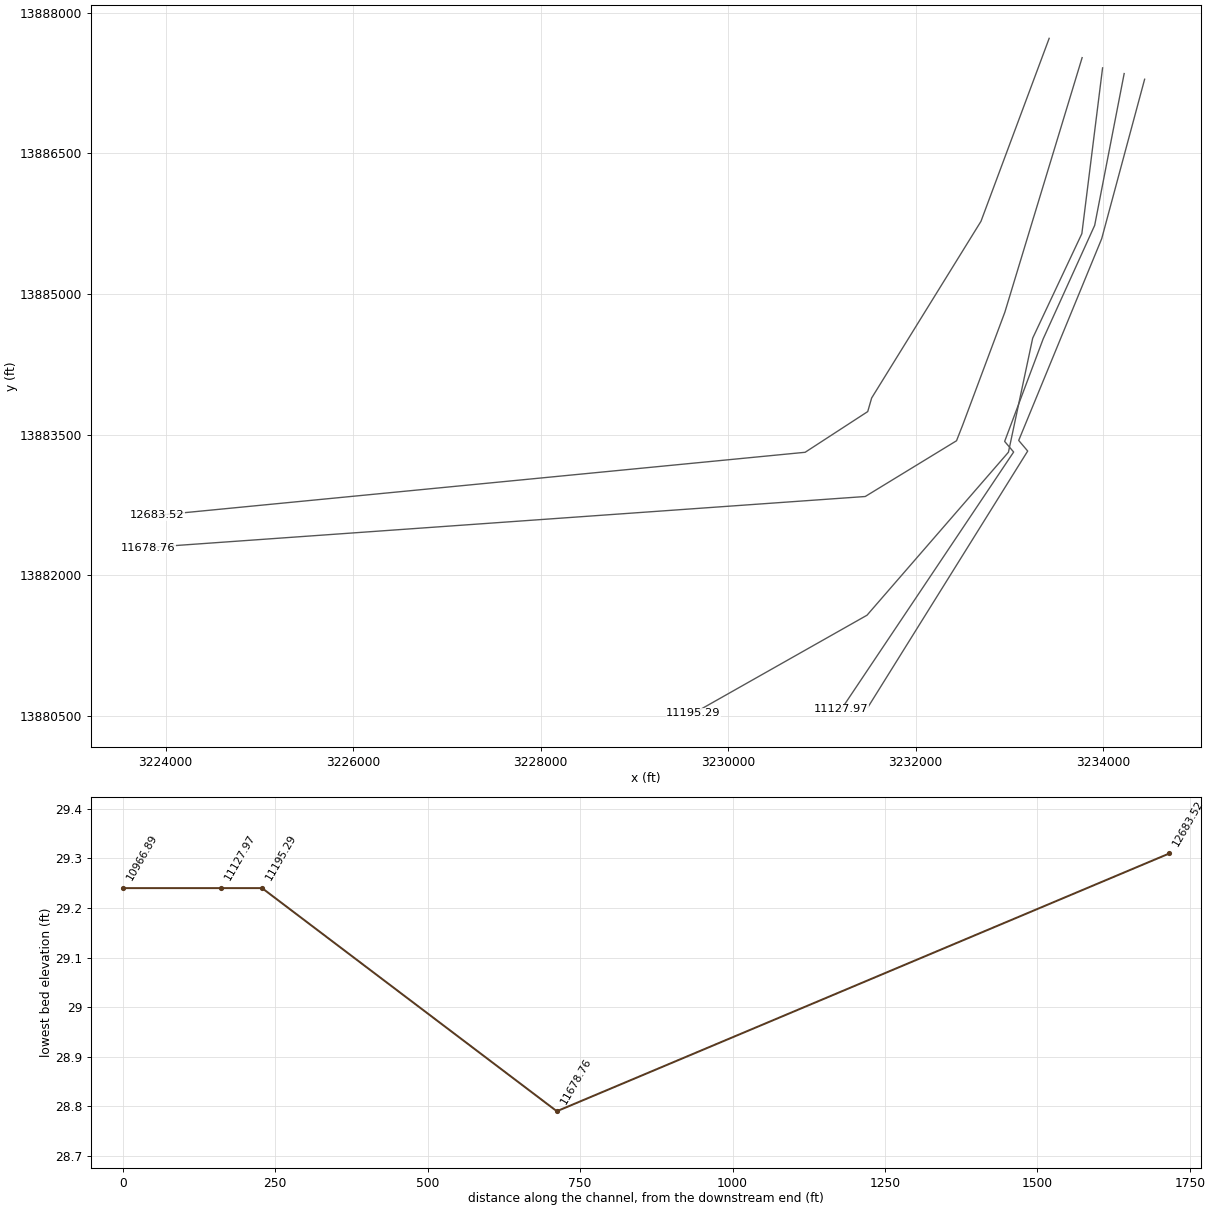
HEC-RAS study Q122-00-00.prj: Q122-00-00

--- Q122-00-00.g01 (geometry) --- (continued)

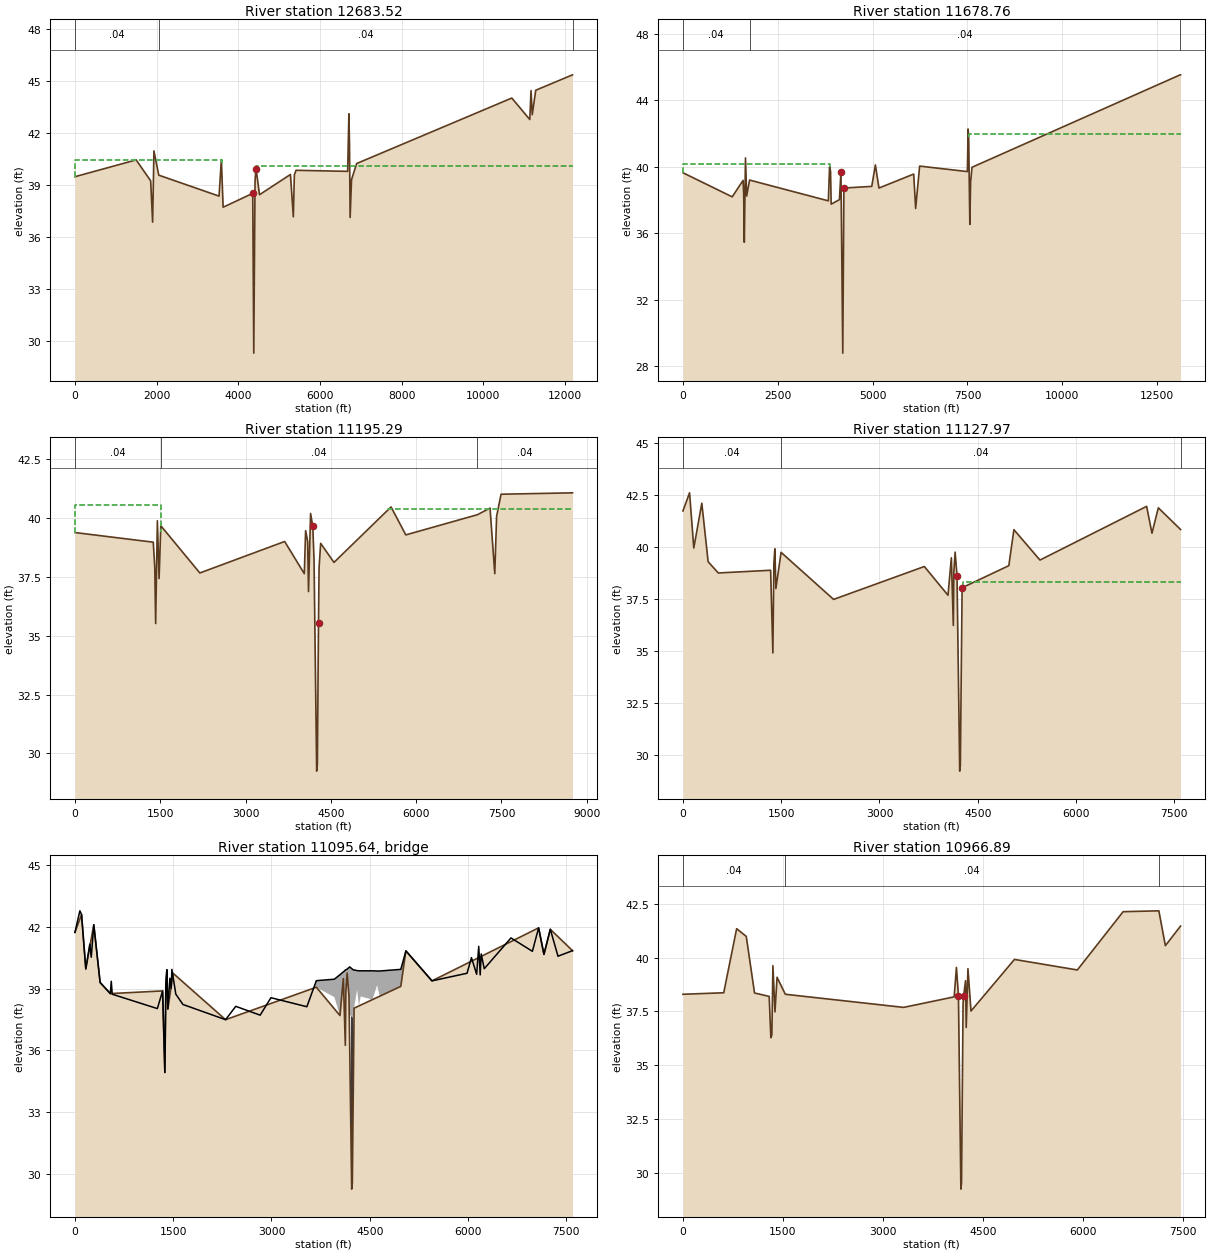
Type RM Length L Ch R = 1 ,12683.52,1004.76,1004.76,1004.76
BEGIN DESCRIPTION:
K
END DESCRIPTION:
XS GIS Cut Line= 6
     3233424.554     13887727.11     3232697.301     13885775.65
     3231531.124    13883890.989     3231489.326    13883746.145
     3230821.727    13883311.987     3223912.218    13882639.702
#Sta/Elev= 30
       0   39.49 1500.04   40.46 1855.41   39.25 1903.44   36.87 1935.45   40.98
 2053.93   39.58 3530.54   38.37 3586.84   40.48 3630.43   37.73 4355.75   38.53
 4380.55   29.31 4412.04   39.31 4436.31   39.96 4521.02   38.45 5279.11   39.62
 5349.74   37.18 5375.05   39.59 5414.75   39.86  6680.7    39.8 6710.84   43.12
 6725.91   41.28 6740.98   37.14 6775.29   39.32 6899.95   40.2510701.26   44.03
11141.67   42.7911171.81   44.4611201.95   43.0711287.23   44.48 12188.1   45.37
#Mann= 3 ,-1 , 0
       0     .04       0 2053.93     .04       0 12188.1     .04       0
#XS Ineff= 2 , 0
       0 3591.67   40.44 4436.34       0    40.1
Permanent Ineff=
       F       F
Bank Sta=4355.75,4436.31
XS Rating Curve= 0
Exp/Cntr=.3,.1

Type RM Length L Ch R = 1 ,11678.76,483.47,483.47,483.47
XS GIS Cut Line= 6
     3233776.059    13887521.055      3232951.84     13884805.98
     3232501.379    13883600.557     3232436.442    13883435.028
     3231462.814      13882840.4     3223809.158    13882296.166
#Sta/Elev= 30
       0   39.64 1298.96   38.19 1585.93   39.18 1601.61   38.35 1617.29   35.46
 1648.64   40.53 1679.99   38.24 1756.45    39.2  3832.6   37.95 3864.91   39.99
 3890.89   39.74 3906.93   37.75 4124.26   38.02 4165.13    39.7 4213.09   28.79
  4242.9   38.72 4977.19   38.82 5072.74   40.11 5166.92   38.72  6082.8   39.56
 6133.74   37.49    6239   40.04 7497.41   39.71 7517.22   42.27 7532.26   41.65
 7562.34   36.53 7582.34   39.09 7619.96   39.9713107.19   45.53 13115.9   45.53
#Mann= 3 ,-1 , 0
       0     .04       0 1756.45     .04       013107.19     .04       0
#XS Ineff= 2 , 0
       0 3880.02   40.17 7528.18       0   41.96
Permanent Ineff=
       F       F
Bank Sta=4165.13,4242.9
XS Rating Curve= 0
Exp/Cntr=.3,.1

Type RM Length L Ch R = 1 ,11195.29,67.32,67.32,67.32
BEGIN DESCRIPTION:
J
END DESCRIPTION:
XS GIS Cut Line= 6
     3233994.235    13887411.967     3233773.101    13885643.712
     3233248.765    13884529.362      3232990.16    13883312.886
     3231481.746    13881574.321     3229630.721    13880527.312
#Sta/Elev= 30
       0   39.39 1377.59   38.98 1404.32    37.9 1419.43   35.52 1449.67   39.89
  1479.9   37.43 1510.13   39.68 2196.61   37.67  3687.7   39.01 4033.32   37.64
 4056.43   39.47 4092.39   39.01  4107.3   36.88 4143.61    40.2 4182.37   39.65
 4204.27   38.24 4250.62   29.24 4262.85   29.53 4282.81   35.55 4292.46   37.88
 4320.83   38.93 4555.17   38.12  5558.4   40.48 5818.03   39.29 7077.83   40.15
 7299.06   40.43  7382.4   37.64 7414.21   40.08 7492.95   41.02 8749.18   41.08
#Mann= 3 ,-1 , 0
       0     .04       0 1510.13     .04       0 7077.83     .04       0
#XS Ineff= 2 , 0
       0 1506.58   40.55 5507.74       0    40.4
Permanent Ineff=
       F       F
Bank Sta=4182.37,4282.81
XS Rating Curve= 0
Exp/Cntr=.5,.3

Type RM Length L Ch R = 1 ,11127.97,161.08,161.08,161.08
XS GIS Cut Line= 6
     3234224.531    13887351.363     3233909.974    13885732.398
     3233360.334    13884520.613     3232949.677    13883427.914
     3233045.622    13883314.837     3231208.652    13880572.473
#Sta/Elev= 30
       0   41.74  101.21   42.61   165.9   39.96  288.15   42.11  384.75    39.3
   540.1   38.76 1338.56   38.89 1373.06   34.92 1388.34   39.23 1403.62   39.92
 1418.91   38.01 1498.45   39.75 2299.97   37.49 3685.44   39.07  4046.5   37.69
  4097.6   39.49 4128.03   36.24 4135.85   38.83 4155.21   39.76 4183.95   38.63
 4225.26   29.24 4234.89   29.53 4261.76   38.05 4974.82   39.11 5052.64   40.84
 5450.52   39.38 7078.65   41.96 7160.09   40.67 7257.14   41.89 7596.22   40.85
#Mann= 3 ,-1 , 0
       0     .04       0 1498.45     .04       0 7596.22     .04       0
#XS Ineff= 2 , 0
       0    4178   38.33    4278       0   38.33
Permanent Ineff=
       F       F
Bank Sta=4183.95,4261.76
XS Rating Curve= 0
Exp/Cntr=.5,.3

Type RM Length L Ch R = 3 ,11095.64,,,
BEGIN DESCRIPTION:
FM 1942 Bridge
END DESCRIPTION:
Bridge Culvert--1,0,-1,-1, 0
Deck Dist Width WeirC Skew NumUp NumDn MinLoCord MaxHiCord MaxSubmerge Is_Ogee
32.33,47.5,2.6,0, 60, 60, , , .95, 0, 0,0,,
       0   75.62  101.21   165.9  227.03  249.08  288.15  384.75   540.1  554.98
  569.63 1258.36 1338.56 1373.06 1388.34 1403.62 1418.91 1449.47 1470.23 1480.03
 1540.45 1649.24 2299.97  2455.1 2827.79 2992.48 3540.66 3685.44 3959.72  4046.5
  4097.6 4116.38 4128.03 4135.85 4155.21 4194.48  4247.3 4307.83 4335.84 4362.89
 4543.28 4613.09 4652.14 4974.82 5052.64 5450.52 5985.83 6053.46 6132.58 6164.67
 6186.75 6202.23 6248.44 6656.16 6983.64 7078.65 7160.09 7257.14 7374.39 7596.22
   41.74   42.79   42.61   39.96   41.17   40.53   42.11    39.3   38.76   39.36
   38.73   38.03   38.89   34.92   39.23   39.92   38.01   39.51   39.02   39.94
   38.73   38.23   37.49   38.14   37.71   38.56   38.12   39.39   39.46   39.68
   39.82   39.86   39.91   39.92   39.95   40.06   39.92   39.88   39.87   39.87
   39.87   39.86   39.86   39.94   40.84   39.38   39.75   40.51    39.7   41.06
   39.67   40.69   39.97   41.47   40.82   41.96   40.67   41.89   40.58   40.85
   41.74   42.79   42.61   39.96   41.17   40.53   42.11    39.3   38.76   39.36
   38.73   38.03   38.89   34.92   39.23   39.92   38.01   39.51   39.02   39.94
   38.73   38.23   37.49   38.14   37.71   38.56   38.12   39.07   38.59   37.69
   39.49   38.54   36.24   38.83   39.76   37.75   37.55   38.96   38.04   38.62
   38.11   39.17   38.41   39.11   40.84   39.38   39.75   40.51    39.7   41.06
   39.67   40.69   39.97   41.47   40.82   41.96   40.67   41.89   40.58   40.85
       0   152.5  234.54  311.33  413.32  611.49   727.1   789.4  804.93  852.97
  898.14  913.67  957.69    1025 1292.76 1302.02 1317.56 1330.28 1348.63 1364.16
 1379.69 1388.09 1410.76  1426.3 1694.28 1784.59 2413.88 3652.99 3737.27 3999.68
 4076.96 4099.33  4144.9 4191.87  4236.3 4246.09  4261.9 4276.33 4289.64 4317.72
 4354.17 4739.21 4969.02 5466.19 5693.82 5770.38 5844.49 5911.78 5939.09 6069.54
 6200.49 6513.95 6597.85 6630.69 6840.43 6867.73 7115.74 7231.34 7426.28 7458.39
    38.3   37.95   38.99   37.99   38.73   38.37    40.9   40.65   41.35   40.46
   41.26   40.27   40.88    38.7    38.2   38.08   36.28   36.25   39.63   39.57
   37.48   38.61   39.09   38.18    38.6   37.79   37.47   38.04   38.61   39.51
    39.9   39.96   39.96   39.92   39.82   39.79   39.75   39.72   39.72   39.72
   39.71   39.68   39.92   39.29   40.03   39.34   40.13   39.43   40.11   39.64
   40.56   40.85   42.14   41.26   41.85   40.61   42.47   40.56   40.57   41.47
    38.3   37.95   38.99   37.99   38.73   38.37    40.9   40.65   41.35   40.46
   41.26   40.27   40.88    38.7    38.2   38.08   36.28   36.25   39.63   39.57
   37.48   38.61   39.09   38.18    38.6   37.79   37.47   38.04   38.61   38.03
   38.32   39.55   37.64   37.64   38.93   36.76   39.18   39.43   39.44   37.52
   38.27   38.36   39.92   39.29   40.03   39.34   40.13   39.43   40.11   39.64
   40.56   40.85   42.14   41.26   41.85   40.61   42.47   40.56   40.57   41.47
Pier Skew, UpSta & Num, DnSta & Num=  ,4216.38, 2 ,4157.101, 2 , 0 , 0 , 0 ,,
    1.51    1.51
   31.34   37.72
    1.51    1.51
   31.34   37.72
Pier Skew, UpSta & Num, DnSta & Num=  ,4234.14, 2 ,4174.879, 2 , 0 , 0 , 0 ,,
    1.51    1.51
   29.52   37.72
    1.51    1.51
   29.52   37.72
BR Coef=-1 , 1 , 1 ,1.25, 0 ,,.34,.8,0,2,0,
WSPro=,,,, 1 ,,,, 0 ,,,, 0 ,,,,-1 ,-1 ,-1 , 0 , 0 , 0 , 0 , 0
BC Design=,, 0 ,, 0 ,,,,,,

Type RM Length L Ch R = 1 ,10966.89,103.75,103.75,103.75
XS GIS Cut Line= 6
     3234442.707    13887290.759     3233984.952    13885590.521
      3233099.56      13883438.3     3233146.464    13883383.019
     3233195.504    13883325.223     3231490.419    13880591.258
#Sta/Elev= 30
       0    38.3  611.49   38.37  804.93   41.35  949.27   40.99 1073.08   38.36
 1292.76    38.2 1317.56   36.28 1333.09   36.41 1348.63   39.63 1379.69   37.48
 1410.76   39.09 1534.92    38.3  3308.1   37.69  4065.5   38.18 4099.33   39.55
 4129.56   38.24 4166.09   29.24 4175.73   29.53 4199.06   37.88 4205.84    38.2
  4236.3   38.93 4246.09   36.76 4272.02   39.49 4317.72   37.52 4969.02   39.92
 5911.78   39.43 6597.85   42.14 7133.53   42.18 7231.34   40.56 7458.39   41.47
#Mann= 3 ,-1 , 0
       0     .04       0 1534.92     .04       0 7133.53     .04       0
#XS Ineff= 2 , 0
       0    4115   38.19 4298.11       0   38.19
Permanent Ineff=
       F       F
Bank Sta=4129.56,4205.84
XS Rating Curve= 0
Exp/Cntr=.5,.3