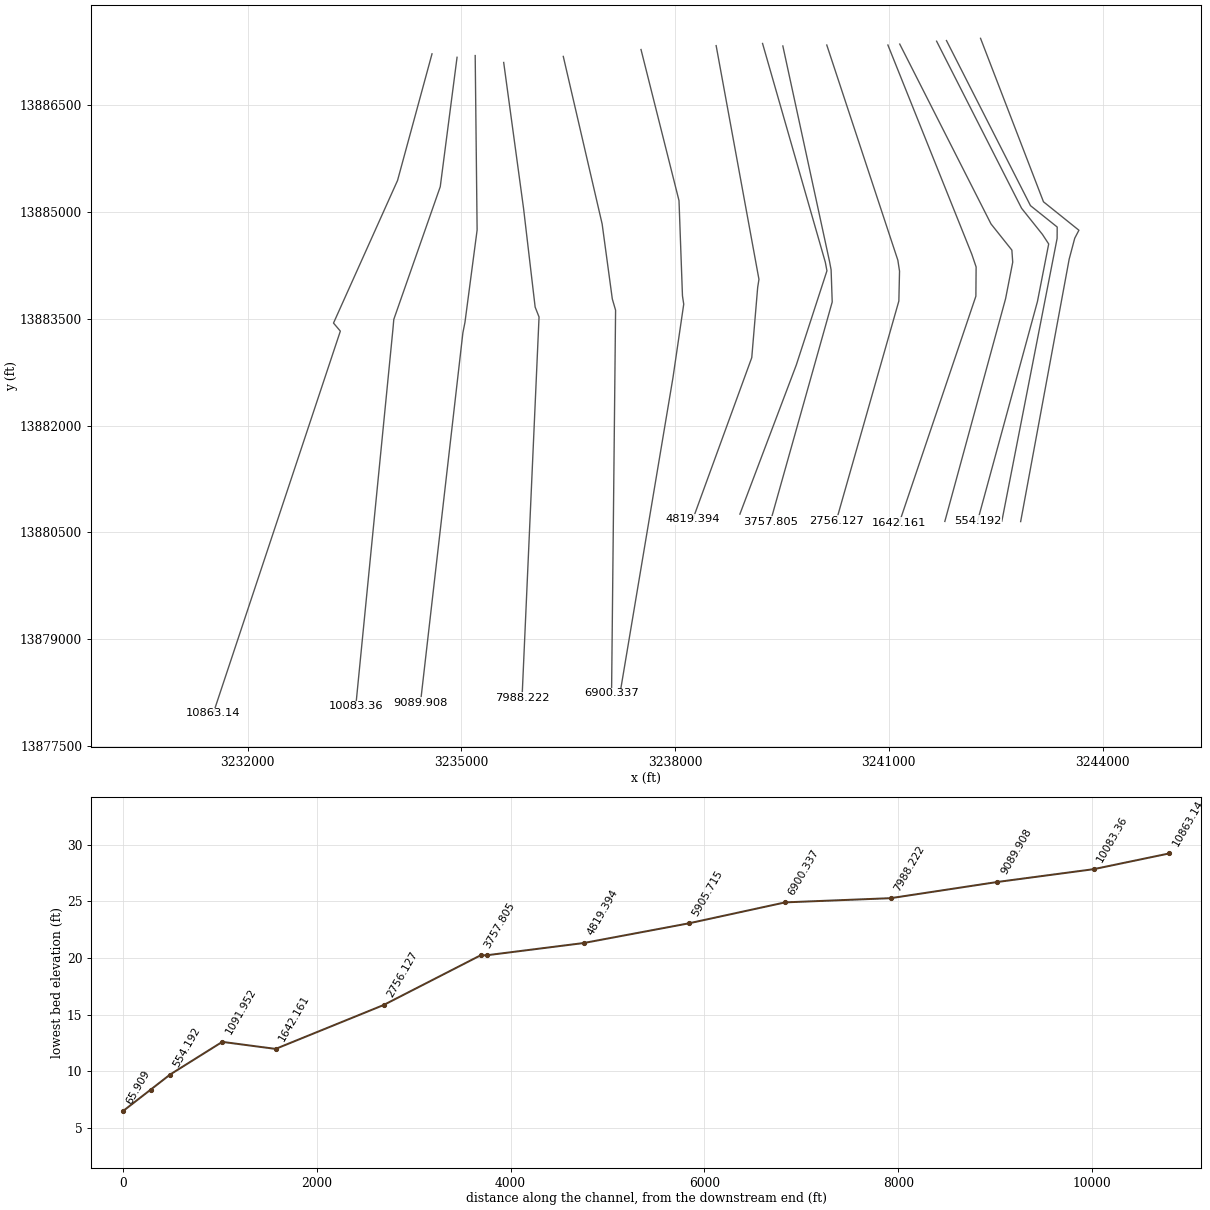
HEC-RAS study Q122-00-00.prj: Q122-00-00

--- Q122-00-00.g01 (geometry) --- (continued)

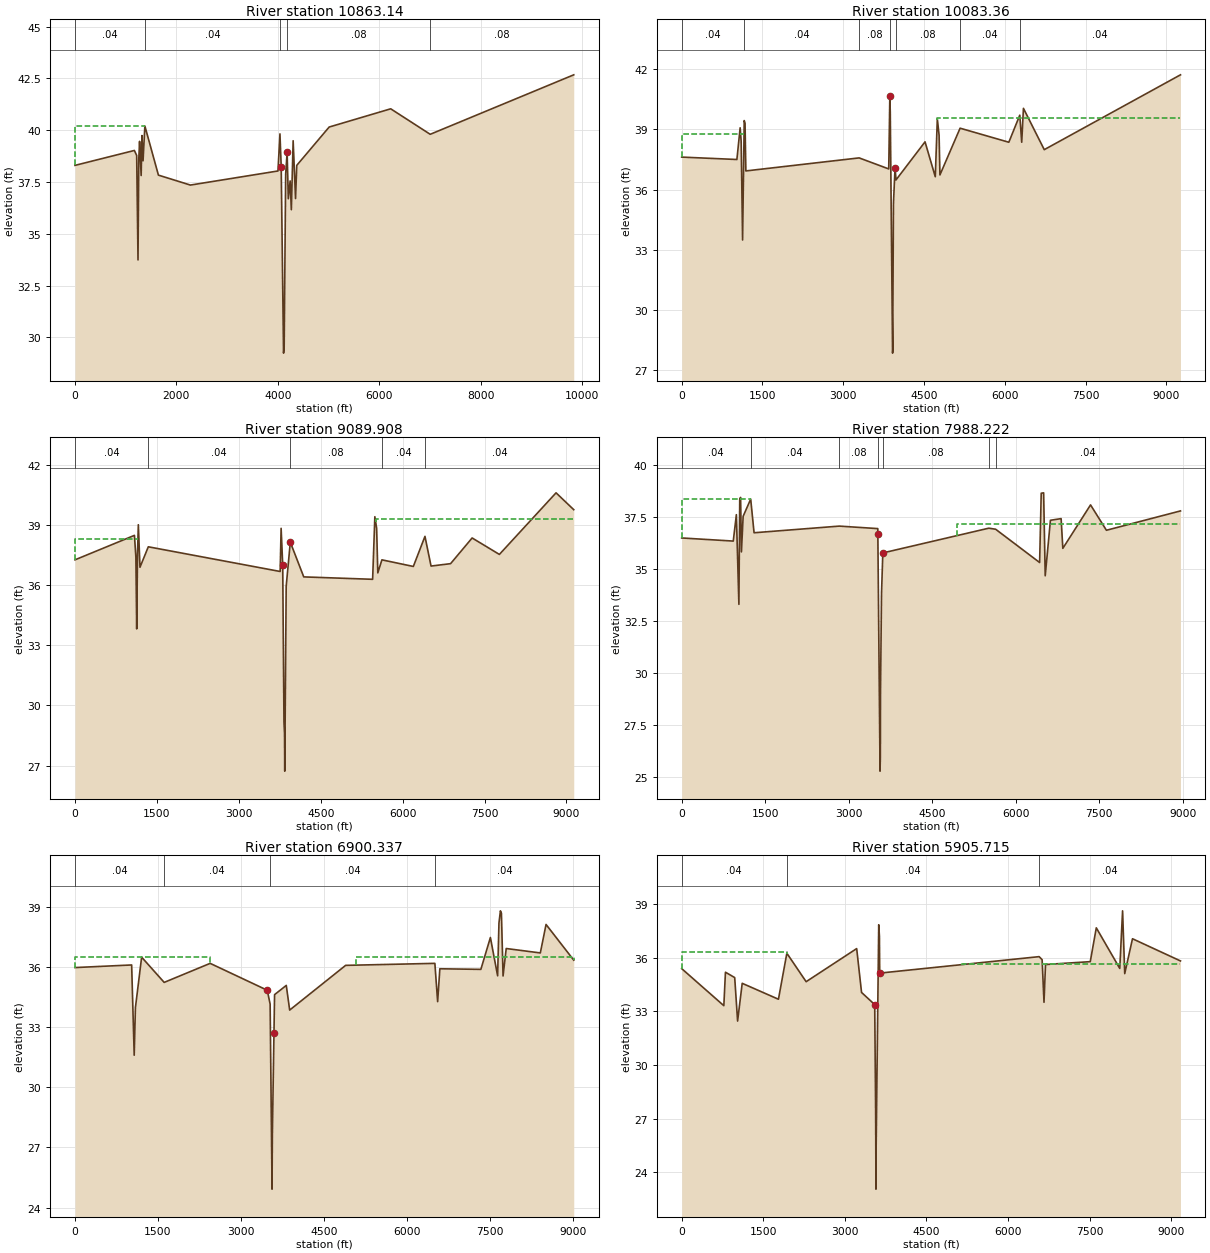
Type RM Length L Ch R = 1 ,10863.14,779.78,779.78,779.78
XS GIS Cut Line= 6
     3234588.157    13887218.033     3234104.484    13885441.186
     3233205.587    13883439.333     3233252.491    13883384.052
     3233301.531    13883326.256     3231517.608    13877961.215
#Sta/Elev= 30
       0    38.3 1171.52   39.02 1217.17   38.78 1243.17   33.74 1258.72   38.62
 1274.27   39.46 1305.36   37.81  1320.9   39.74 1342.56   38.52  1378.7    40.2
 1645.82   37.83 2277.02   37.35 4004.03   38.03 4042.97   39.82 4067.64   38.24
    4114   29.24 4126.22   29.53 4155.84   37.88 4172.22   38.48 4184.21   38.93
 4208.18   36.69 4243.95   37.55 4267.68   36.16 4303.16   39.49 4350.72    36.7
 4374.45    38.3 5013.59   40.15 6227.84   41.03 7007.05    39.8 9838.06   42.67
#Mann= 5 ,-1 , 0
       0     .04       0  1378.7     .04       0 4042.97     .04       0
 4172.22     .08       0 7007.05     .08       0
#XS Ineff= 2 , 0
       0  1378.7    40.2 6000.99       0    40.3
Permanent Ineff=
       F       F
Bank Sta=4067.64,4184.21
XS Rating Curve= 0
Exp/Cntr=.3,.1

Type RM Length L Ch R = 1 ,10083.36,993.46,993.46,993.46
BEGIN DESCRIPTION:
I
END DESCRIPTION:
XS GIS Cut Line= 6
     3234939.663     13887169.55     3234703.846    13885353.352
     3234051.641    13883490.594     3234042.424    13883385.725
     3234039.614    13883353.762      3233517.99    13878061.906
#Sta/Elev= 30
       0   37.62 1024.57    37.5 1085.08   39.08 1104.01    38.4 1130.46   33.49
 1160.71   39.44 1175.83    39.3 1190.96   36.93 3294.32   37.58 3843.52   37.03
 3863.99   40.64 3872.16   39.86 3914.86   27.85 3920.01      28 3920.06   29.68
 3931.18   35.31 3961.03    37.1 3978.11   36.48 4517.69   38.38 4707.96   36.64
 4745.73   39.52 4778.65   38.71 4794.13   36.73 5168.61   39.06  6073.5   38.36
 6276.65   39.71 6312.43   38.36 6344.53   40.05 6731.09   37.99 9259.94   41.72
#Mann= 7 ,-1 , 0
       0     .04       0 1160.71     .04       0 3294.32     .08       0
 3863.99     .04       0 3978.11     .08       0 5168.61     .04       0
 6276.65     .04       0
#XS Ineff= 2 , 0
       0 1157.56   38.75 4748.72       0   39.57
Permanent Ineff=
       F       F
Bank Sta=3863.99,3961.03
XS Rating Curve= 0
Exp/Cntr=.3,.1

Type RM Length L Ch R = 1 ,9089.908,1101.69,1101.69,1101.69
BEGIN DESCRIPTION:
H
END DESCRIPTION:
XS GIS Cut Line= 6
     3235194.201    13887193.792     3235221.167    13884745.017
     3235050.296    13883447.562     3235021.557    13883303.603
     3234721.347     13880685.18     3234425.821    13878107.602
#Sta/Elev= 30
       0   37.25 1089.12   38.47 1115.35   37.39 1130.36   33.81 1145.36   37.56
 1160.36      39 1190.36   36.88 1343.02    37.9 3757.58   36.67 3775.08   38.82
  3804.4      37 3827.48   29.16  3837.5   28.61  3841.8   26.72 3868.01   35.93
 3943.46   38.13 4189.74    36.4 5451.18   36.28 5491.81    39.4 5524.45   38.82
    5546    36.6 5621.05   37.25 6196.51   36.92 6409.55   38.42 6520.89   36.94
 6878.84   37.06 7273.38   38.34 7772.62   37.52 8810.41   40.59 9134.42   39.75
#Mann= 5 ,-1 , 0
       0     .04       0 1343.02     .04       0 3943.46     .08       0
 5621.05     .04       0 6409.55     .04       0
#XS Ineff= 2 , 0
       0 1153.52   38.29 5505.68       0   39.27
Permanent Ineff=
       F       F
Bank Sta=3804.4,3943.46
XS Rating Curve= 0
Exp/Cntr=.3,.1

Type RM Length L Ch R = 1 ,7988.222,1087.89,1087.89,1087.89
BEGIN DESCRIPTION:
G
END DESCRIPTION:
XS GIS Cut Line= 6
      3235594.19    13887096.825      3235872.97    13885048.397
     3236035.645    13883663.538     3236064.764    13883589.645
     3236090.382    13883524.632     3235851.786    13878179.379
#Sta/Elev= 30
       0    36.5   926.4   36.35  982.29   37.62 1027.71   33.31 1042.85   38.36
 1057.98   38.45 1073.12   35.83 1103.82   37.54 1239.64   38.37  1300.2   36.75
 2831.33   37.07 3523.16   36.95 3524.23   36.67 3563.64   25.29 3569.34   25.95
 3571.57   29.03  3590.2   33.83 3613.57   35.78 5517.38   36.97 5640.21   36.92
 6430.83   35.32 6459.57   38.65 6502.69   38.67 6531.44   34.68 6625.12   37.35
 6816.89   37.43 6847.88      36 7345.83   38.09 7631.12   36.87 8961.57    37.8
#Mann= 7 ,-1 , 0
       0     .04       0 1239.64     .04       0 2831.33     .08       0
 3523.16     .04       0 3613.57     .08       0 5517.38     .04       0
 5640.21     .04       0
#XS Ineff= 2 , 0
       0 1239.64   38.37  4954.6       0   37.15
Permanent Ineff=
       F       F
Bank Sta=3524.23,3613.57
XS Rating Curve= 0
Exp/Cntr=.3,.1

Type RM Length L Ch R = 1 ,6900.337,994.62,994.62,994.62
BEGIN DESCRIPTION:
F
END DESCRIPTION:
XS GIS Cut Line= 6
      3236430.53    13887181.671     3236975.969    13884830.222
      3237118.63    13883777.763     3237143.004    13883694.079
      3237164.67    13883619.697     3237108.103    13878242.616
#Sta/Elev= 30
       0   35.97 1024.67    36.1 1070.86    31.6 1092.72   33.97 1205.21   36.49
  1612.8   35.23 2443.99   36.18 3475.96   34.84 3528.37   34.15 3563.13   24.92
 3568.74   27.64 3597.81   32.71 3608.78   34.62 3820.37   35.08  3881.8   33.85
 4893.66   36.08 6506.95   36.18 6557.04   34.27 6596.95   35.91 7338.53   35.88
 7510.96   37.47 7641.44   35.56 7665.61   38.19 7692.01    38.8 7710.14   38.68
 7739.83   35.55 7797.02   36.92 8413.57    36.7 8517.06   38.12 9017.97   36.34
#Mann= 4 ,-1 , 0
       0     .04       0  1612.8     .04       0 3528.37     .04       0
 6506.95     .04       0
#XS Ineff= 2 , 0
       0 2441.26   36.49 5081.43       0    36.5
Permanent Ineff=
       F       F
Bank Sta=3475.96,3597.81
XS Rating Curve= 0
Exp/Cntr=.3,.1

Type RM Length L Ch R = 1 ,5905.715,1086.32,1086.32,1086.32
BEGIN DESCRIPTION:
E
END DESCRIPTION:
XS GIS Cut Line= 6
     3237521.409    13887278.638     3238054.727    13885157.485
      3238103.36    13883821.025     3238121.051    13883704.282
     3237969.881    13882672.706     3237228.124    13878248.657
#Sta/Elev= 30
       0   35.39  774.72   33.32  804.41   35.19  974.55   34.89 1027.85   32.46
 1112.55   34.57 1778.83   33.68 1933.49   36.25    2288   34.66 3217.35   36.51
 3306.89   34.06 3548.83   33.38 3566.09   27.39 3571.82   23.07 3575.04   23.79
 3575.32   25.45 3622.73   37.84 3635.63    37.2 3640.51   35.14  6572.1   36.06
 6627.11   35.89 6661.59   33.51 6689.35   35.62 7512.17   35.78 7623.36   37.67
 8054.74    35.4 8106.48   38.62 8145.92   35.11 8288.82   37.06 9170.99   35.82
#Mann= 3 ,-1 , 0
       0     .04       0 1933.49     .04       0  6572.1     .04       0
#XS Ineff= 2 , 0
       0 1942.45   36.32 5155.19       0   35.64
Permanent Ineff=
       F       F
Bank Sta=3548.83,3640.51
XS Rating Curve= 0
Exp/Cntr=.3,.1

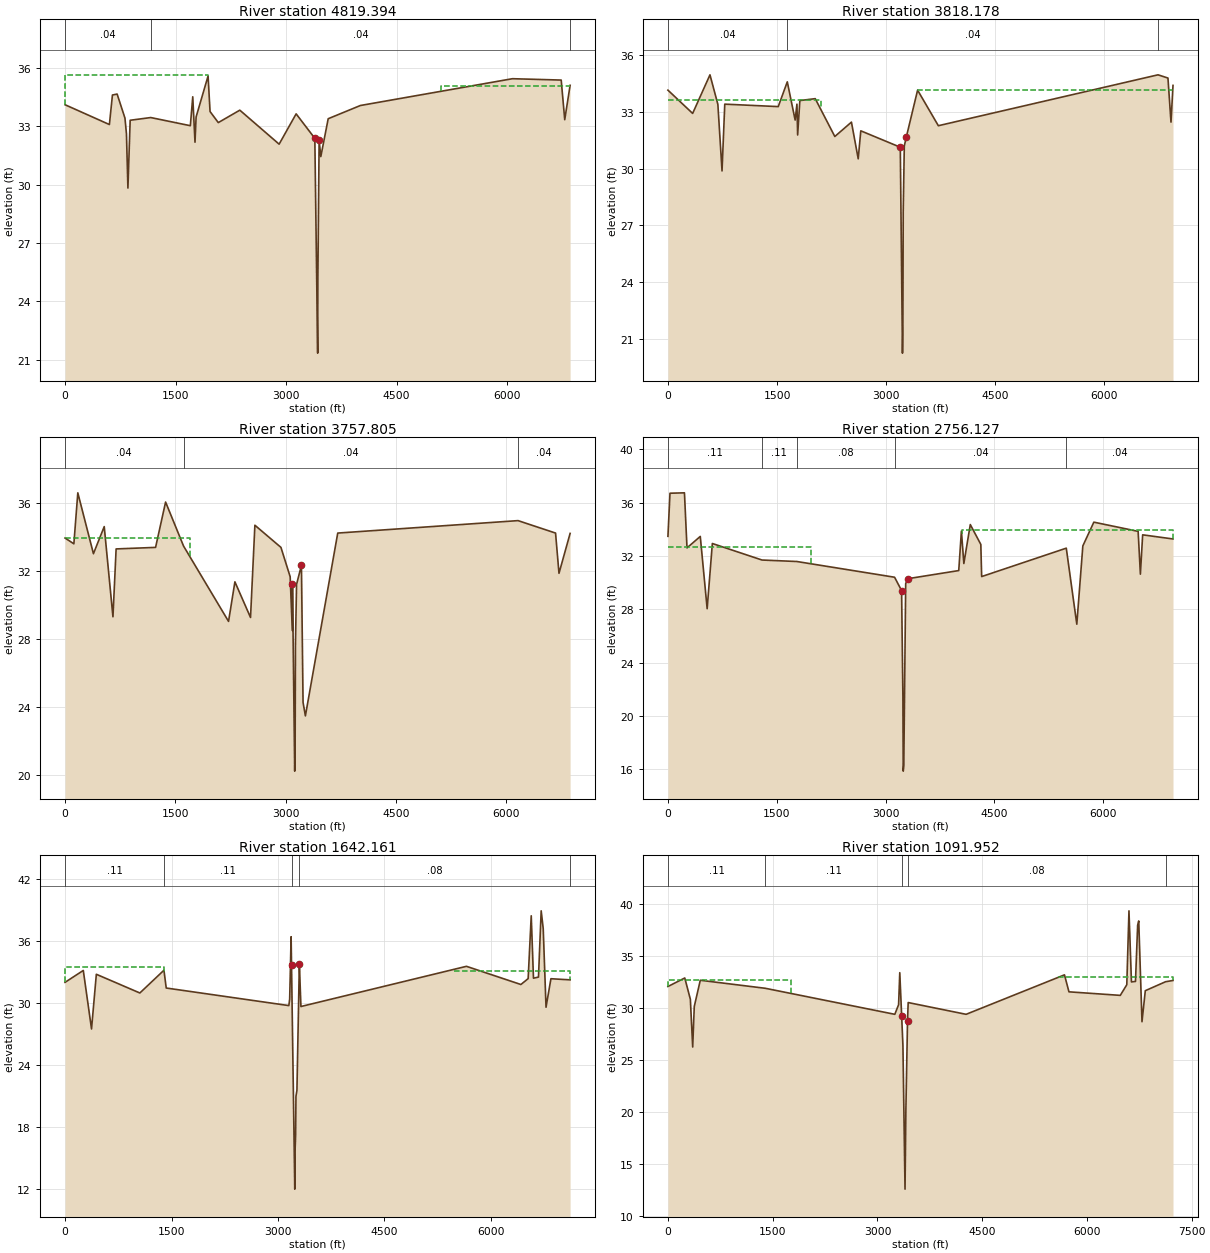
Type RM Length L Ch R = 1 ,4819.394,1001.22,1001.22,1001.22
BEGIN DESCRIPTION:
D
END DESCRIPTION:
XS GIS Cut Line= 6
     3238575.925    13887333.182     3239176.851    13884052.845
     3239161.702    13883957.977     3239159.047    13883941.344
     3239075.911    13882954.517     3238248.661    13880684.883
#Sta/Elev= 30
       0   34.12  601.95    33.1  643.18   34.62  706.78   34.67   813.2   33.43
  833.32   32.62  853.18   29.83  883.78   33.32 1162.77   33.46 1700.35   33.04
 1733.04   34.53 1763.54   32.19 1778.48   33.49 1940.96    35.6 1967.77   33.77
 2079.67    33.2 2371.68   33.84  2905.1   32.09 3136.01   33.65 3389.67   32.39
 3428.19   21.33 3430.99   25.19 3447.84   32.28 3470.76   31.45 3571.12    33.4
 4007.61   34.08 6071.05   35.46 6732.92   35.39 6780.82   33.35 6853.86   35.12
#Mann= 3 ,-1 , 0
       0     .04       0 1162.77     .04       0 6853.86     .04       0
#XS Ineff= 2 , 0
       0  1941.3   35.66 5096.01       0   35.08
Permanent Ineff=
       F       F
Bank Sta=3389.67,3447.84
XS Rating Curve= 0
Exp/Cntr=.3,.1

Type RM Length L Ch R = 1 ,3818.178,60.37,60.37,60.37
BEGIN DESCRIPTION:
C
END DESCRIPTION:
XS GIS Cut Line= 6
     3239227.421    13887363.484     3240108.437    13884292.739
     3240113.065    13884268.218     3240131.037    13884173.009
     3239701.354    13882852.005     3238909.249    13880757.608
#Sta/Elev= 30
       0   34.15  339.88   32.92  578.07   34.96  686.59    33.4  743.82   29.88
  781.59   33.41 1516.81   33.28 1641.24   34.59 1749.12   32.57 1773.76   33.41
 1783.58   31.78 1814.05    33.6 2025.43    33.7 2294.73    31.7 2523.27   32.46
 2616.44   30.52 2651.98      32 3190.36   31.14 3194.63   31.24 3224.87   20.25
 3230.53   21.37 3235.23   27.73 3250.15    31.2  3277.1   31.66 3432.96   34.15
 3718.24   32.27 6738.67   34.96 6875.39   34.79  6917.1   32.46 6944.78    34.4
#Mann= 3 ,-1 , 0
       0     .04       0 1641.24     .04       0 6738.67     .04       0
#XS Ineff= 2 , 0
       0 2100.45   33.65 3436.87       0   34.14
Permanent Ineff=
       F       F
Bank Sta=3190.36,3277.1
XS Rating Curve= 0
Exp/Cntr=.3,.1

Type RM Length L Ch R = 1 ,3757.805,1001.68,1001.68,1001.68
BEGIN DESCRIPTION:
B
END DESCRIPTION:
XS GIS Cut Line= 6
     3239512.179    13887328.372     3240166.923     13884306.06
     3240171.551    13884281.539     3240189.523     13884186.33
     3240205.061    13883735.802     3239337.919    13880652.893
#Sta/Elev= 30
       0   33.92  120.02   33.58   173.6   36.57  386.09      33  532.84   34.59
  651.45    29.3  694.51   33.28 1231.03   33.37 1367.25   36.03 1611.18   33.45
 2223.19   29.03 2309.69   31.35 2522.04   29.26 2581.44   34.67 2935.67   33.37
 3060.99   31.65 3089.92    28.5 3092.42   31.24 3122.66   20.25 3128.32   21.37
 3133.02   27.73 3147.94    31.2 3214.26   32.32 3236.33   24.28 3268.15   23.49
 3708.03   34.21 6159.55   34.94 6669.59   34.21 6716.33   31.85  6867.6   34.19
#Mann= 3 ,-1 , 0
       0     .04       0 1611.18     .04       0 6159.55     .04       0
#XS Ineff= 2 , 0
       0 1695.82   33.91 3762.81       0   34.06
Permanent Ineff=
       F       F
Bank Sta=3092.42,3214.26
XS Rating Curve= 0
Exp/Cntr=.3,.1

Type RM Length L Ch R = 1 ,2756.127,1113.97,1113.97,1113.97
BEGIN DESCRIPTION:
A
END DESCRIPTION:
XS GIS Cut Line= 6
     3240128.789    13887341.776     3241126.227    13884321.698
     3241135.536    13884261.288     3241149.935    13884167.861
     3241140.484    13883749.207     3240262.835    13880666.297
#Sta/Elev= 30
       0   33.47   28.39    36.7  227.61   36.73  262.79    32.6  445.76   33.46
  540.54   28.04  612.13   32.93 1296.55   31.69 1775.65   31.58 3123.44    30.4
    3220    29.4 3238.25   21.42 3242.56   15.86 3250.49   16.28 3276.64   29.92
 3305.68   30.29 4007.79    30.9 4044.24   33.86 4077.99   31.43 4166.91   34.35
 4311.93   32.86 4323.46   30.45 5489.68   32.58 5634.57   26.88 5717.85   32.75
 5869.44   34.53 6479.77   33.84 6510.97   30.63 6542.16   33.58 6960.35   33.27
#Mann= 5 ,-1 , 0
       0     .11       0 1296.55     .11       0 1775.65     .08       0
 3123.44     .04       0 5489.68     .04       0
#XS Ineff= 2 , 0
       0 1966.04   32.68 4047.18       0   33.96
Permanent Ineff=
       F       F
Bank Sta=3220,3305.68
XS Rating Curve= 0
Exp/Cntr=.3,.1

Type RM Length L Ch R = 1 ,1642.161,550.21,550.21,550.21
XS GIS Cut Line= 6
     3240986.682    13887341.776     3242164.681    13884404.202
     3242188.879    13884332.736     3242224.914    13884226.315
     3242221.397     13883816.36     3241147.537    13880639.488
#Sta/Elev= 30
       0      32  257.08   33.15  373.23   27.49  440.93   32.78 1054.16   30.97
 1393.38   33.17  1425.7   31.45 3153.24   29.75 3164.97   30.38 3185.24   36.41
 3190.98   33.64 3236.93   11.99 3240.42    15.6 3248.67   17.24  3253.6   20.98
 3267.19   21.54  3296.8   32.23  3301.8   33.78 3323.34   29.66 5655.63   33.55
 6422.74   31.79 6525.02   32.36 6568.34   38.44 6600.01    32.4 6670.44   32.51
 6708.55   38.92 6737.13   37.21 6776.85   29.59 6845.88   32.35 7116.21   32.24
#Mann= 5 ,-1 , 0
       0     .11       0 1393.38     .11       0 3190.98     .04       0
  3296.8     .08       0 7116.21     .08       0
#XS Ineff= 2 , 0
       0 1395.71   33.49 5486.68       0   33.14
Permanent Ineff=
       F       F
Bank Sta=3190.98,3301.8
XS Rating Curve= 0
Exp/Cntr=.3,.1

Type RM Length L Ch R = 1 ,1091.952,537.76,537.76,537.76
XS GIS Cut Line= 6
     3241152.843    13887354.809     3242433.669    13884830.856
     3242726.557    13884463.365     3242738.548    13884293.644
     3242638.195    13883780.628     3241785.705    13880655.053
#Sta/Elev= 30
       0   32.07  241.24   32.89  321.06   30.85   354.7   26.26  377.23   30.15
  463.36   32.67 1394.13    31.9 3248.94    29.4 3303.17   30.32 3320.18    33.4
 3346.88   29.27  3365.3   26.41 3395.37   12.61 3407.71   20.29 3431.14   28.78
 3440.48   30.53 4270.04    29.4 5678.76   33.19  5742.9   31.56 6477.84   31.22
 6571.13   32.24 6602.23   39.34 6637.76   32.51 6695.51   32.56 6726.61   37.96
 6742.16   38.37  6788.8   28.69 6836.35   31.67 7126.38   32.53  7232.9   32.65
#Mann= 5 ,-1 , 0
       0     .11       0 1394.13     .11       0 3346.88     .04       0
 3431.14     .08       0 7126.38     .08       0
#XS Ineff= 2 , 0
       0 1761.61   32.69 5588.24       0   32.99
Permanent Ineff=
       F       F
Bank Sta=3346.88,3431.14
XS Rating Curve= 0
Exp/Cntr=.3,.1

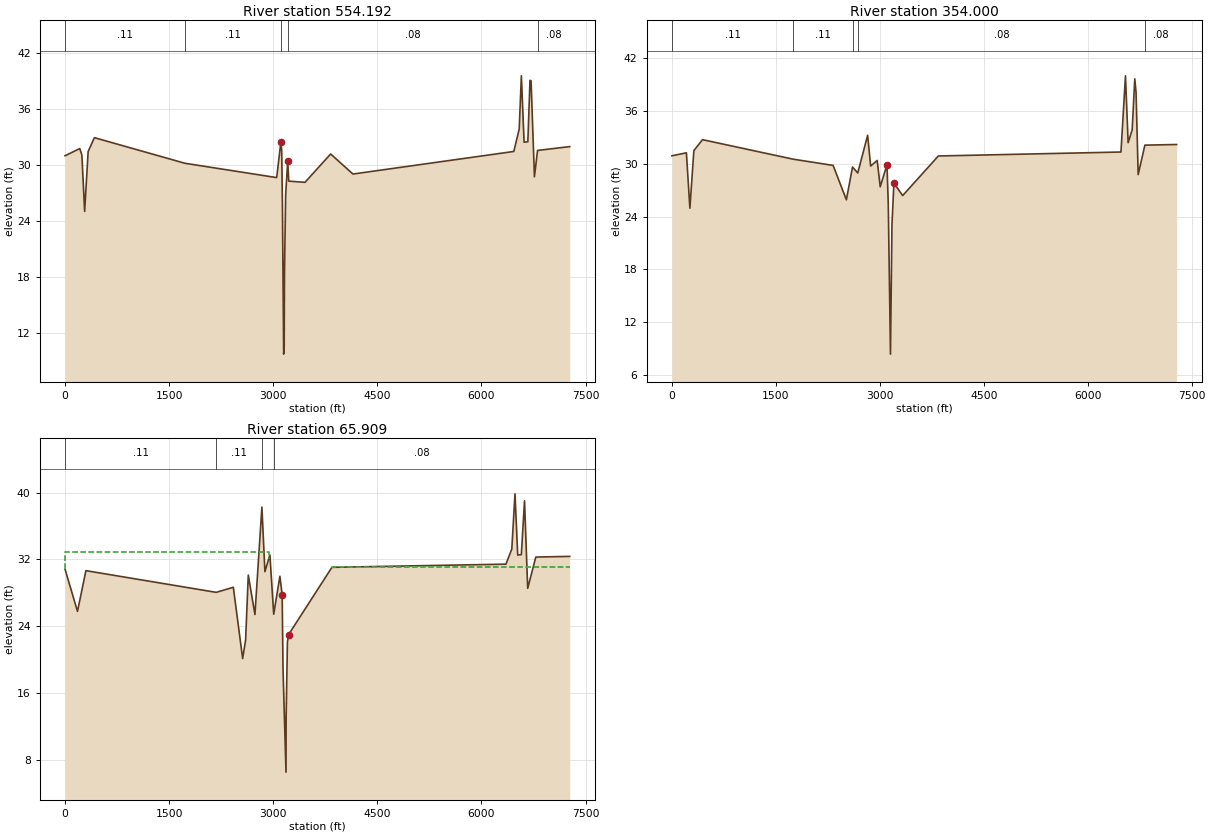
Type RM Length L Ch R = 1 ,554.192 ,200.19,200.19,200.19
XS GIS Cut Line= 6
     3241670.315    13887395.395     3242863.323    13885049.594
     3243156.471     13884682.51     3243243.437    13884549.439
     3243085.672    13883742.266     3242246.712    13880666.297
#Sta/Elev= 30
       0      31   212.6   31.77  242.94   31.07  282.59   25.03  333.04   31.45
  422.93   32.94 1729.84   30.19 3049.05   28.66 3109.92   32.47 3121.59   31.54
 3132.05   25.76 3150.11    9.73  3157.6   10.58  3161.6   18.41 3178.91   26.85
 3208.44   30.43  3223.1   28.28 3457.07   28.15 3826.93   31.19 4148.24   29.04
 6465.72   31.46  6543.4   33.87 6574.49   39.57  6613.9   32.45 6667.78    32.5
 6698.88   39.09 6714.42   39.03 6762.73   28.75 6807.71   31.57 7271.25   31.98
#Mann= 5 ,-1 , 0
       0     .11       0 1729.84     .11       0 3109.92     .04       0
 3208.44     .08       0 6807.71     .08       0
Bank Sta=3109.92,3208.44
XS Rating Curve= 0
Exp/Cntr=.3,.1

Type RM Length L Ch R = 1 ,354.000 ,288.09,288.09,288.09
XS GIS Cut Line= 6
     3241808.694    13887404.419     3242988.076     13885086.99
     3243362.836    13884787.209     3243362.259    13884715.196
     3243361.553    13884627.011     3242585.945    13880658.759
#Sta/Elev= 30
       0   30.89   208.8   31.23   259.1   24.95  316.52   31.48  441.05   32.72
  1748.2   30.51 2326.21    29.8 2517.59    25.9 2606.18   29.62 2681.65   28.94
  2824.4   33.22 2867.64   29.73 2962.08   30.36 3005.93   27.38 3103.45   29.86
 3122.19   25.43 3153.89     8.4 3175.35   23.06 3203.36    27.8 3330.06   26.38
 3844.84   30.87 6480.37   31.32 6545.27   39.96 6583.83   32.38  6642.2   33.84
 6679.68   39.62  6698.1   38.08 6728.67   28.76 6825.51    32.1 7283.73   32.17
#Mann= 5 ,-1 , 0
       0     .11       0  1748.2     .11       0 2606.18     .04       0
 2681.65     .08       0 6825.51     .08       0
Bank Sta=3103.45,3203.36
XS Rating Curve= 0
Exp/Cntr=.3,.1

Type RM Length L Ch R = 1 ,65.909  ,65.91,65.91,65.91
XS GIS Cut Line= 6
     3242286.926    13887435.608     3243170.132    13885141.564
     3243667.614    13884742.002     3243609.175    13884630.908
     3243530.906    13884336.293     3242849.918    13880652.893
#Sta/Elev= 30
       0   30.82  179.84   25.76   300.9   30.64  2178.8   28.04  2425.3   28.65
 2559.49   20.11 2602.16   22.33 2640.66   30.11 2736.48   25.38  2836.9   38.26
 2880.21   30.52 2952.07   32.53 3006.91   25.42 3096.26   29.97 3128.98   27.73
 3141.25   18.84 3184.33    6.49 3185.94   12.99 3204.45   22.09 3221.79   22.98
 3845.94   31.04 6353.17   31.42 6437.93   33.24 6483.69   39.85 6523.06   32.51
 6575.21   32.56 6620.98   39.01 6666.74   28.52 6783.71   32.27 7272.44   32.35
#Mann= 4 ,-1 , 0
       0     .11       0  2178.8     .11       0  2836.9     .04       0
 3006.91     .08       0
#XS Ineff= 2 , 0
       0 2934.71   32.85 3843.43       0   31.12
Permanent Ineff=
       F       F
Bank Sta=3128.98,3221.79
XS Rating Curve= 0
Exp/Cntr=.3,.1

Chan Stop Cuts=-1